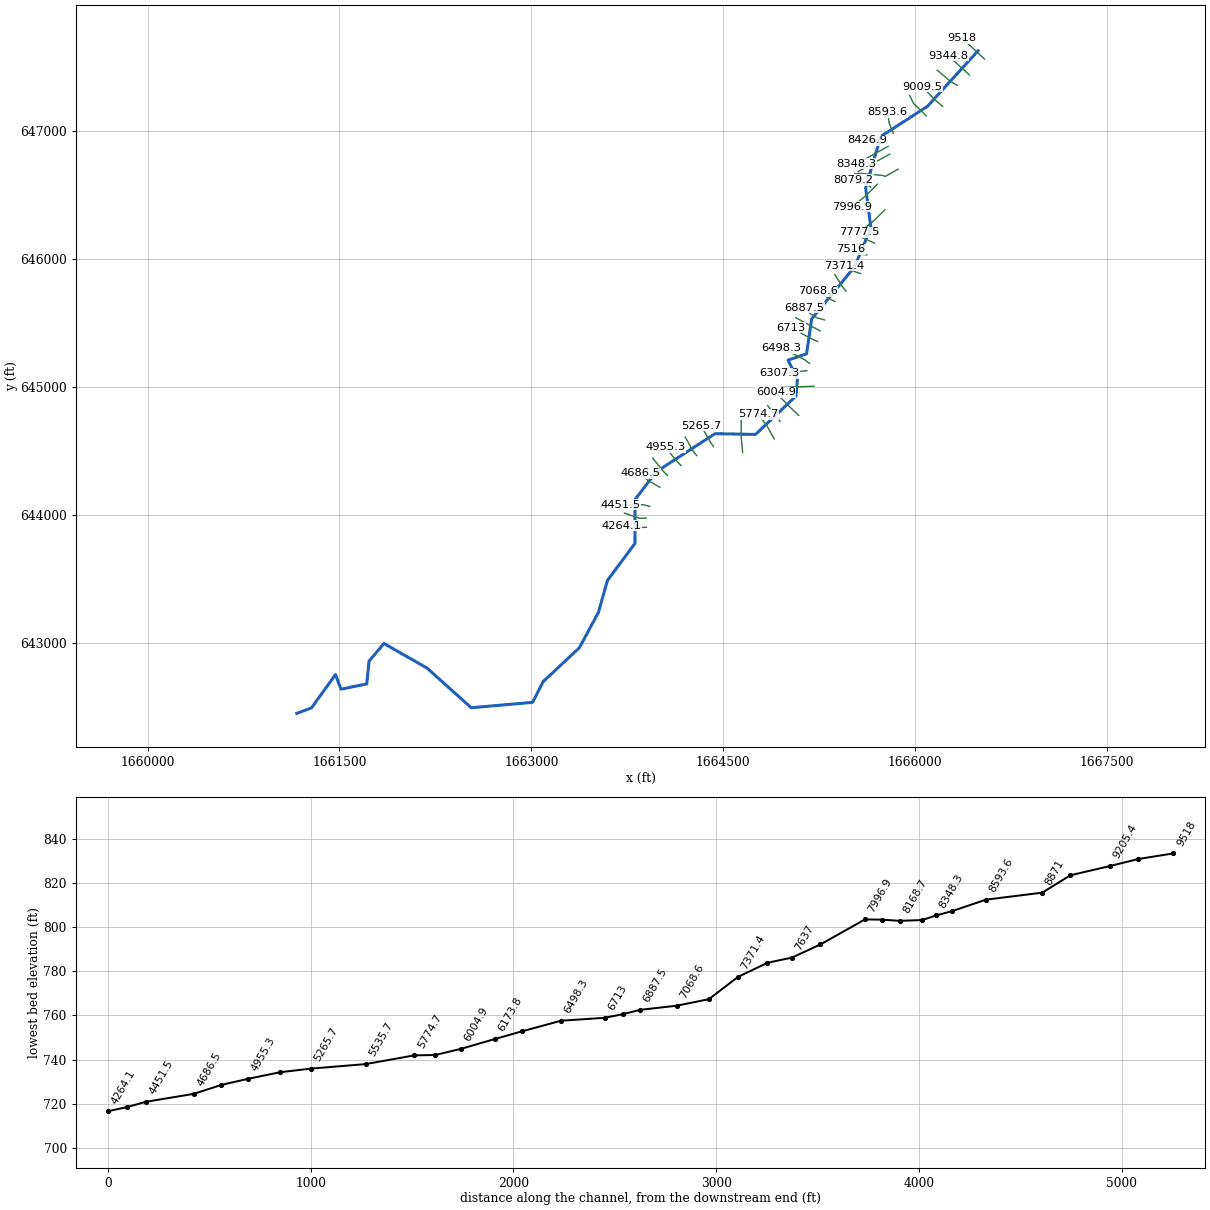
--- PNTRSRN.prj (project) ---

Proj Title=PNTRSRN
Current Plan=p01
Default Exp/Contr=0,0
English Units
Geom File=g01
Flow File=f01
Plan File=p01
BEGIN DESCRIPTION:
END DESCRIPTION:
DSS Export Rating Curves= 0
DSS Export Rating Curve Sorted= 0
DSS Export Volume Flow Curves= 0
DXF Filename=..\..\..\..\..\Engineering\Hydraulics\PNTRSRN\PNTRSRN.
DXF OffsetX= 0
DXF OffsetY= 0
DXF ScaleX= 0
DXF ScaleY= 0

--- PNTRSRN.p01 (plan) ---

Plan Title=Floodplain
Program Version=4.00
Geom File=g01
Flow File=f01
K Sum by GR=0
Std Step Tol=0.01
Critical Tol=0.01
Num of Std Step Trials=20
Max Error Tol=0.3
Flow Tol Ratio=0.001
Split Flow NTrial=30
Split Flow Tol=0.02
Split Flow Ratio=0.02
Log Output Level=0
Friction Slope Method=1
Unsteady Friction Slope Method=2
Unsteady Bridges Friction Slope Method=1
Global Log Level=0
CheckData=False
Run HTab=0
Run UNet=0
Run PostProcess=0
UNET Theta=0
UNET Theta Warmup=0
UNET ZTol=0
UNET ZSATol=0
UNET MxIter=0
UNET MaxInSteps=0
UNET DtIC=0
UNET DtMin=0
UNET MaxCRTS=0
UNET WFStab=0
UNET SFStab=0
UNET WFX=0
UNET SFX=0
UNET DSS MLevel=0
UNET DZMax Abort=0
UNET Convert EG Bridges=0
UNET Use Existing IB Tables=0
UNET Froude Limit=0
UNET Froude Power=0
Write IC File=0
Echo Input=False
Echo Output=False
Write Detailed=0

--- PNTRSRN.f01 (steady flow) ---

Flow Title=NFF Regression Equation
Program Version=4.10
Number of Profiles= 1
Profile Names=P100yr
River Rch & RM=PNTRSRN,Main            ,9518
881.7515
River Rch & RM=PNTRSRN,Main            ,8426.9
 950.767
River Rch & RM=PNTRSRN,Main            ,4041.9
1055.406
River Rch & RM=PNTRSRN,Main            ,650
1171.506
Boundary for River Rch & Prof#=PNTRSRN,Main            , 1
Up Type= 0
Dn Type= 3
Dn Slope=0.006
DSS Import GetInterval= 0
DSS Import GetPeak= 0
DSS Import FillOption= 0

--- PNTRSRN.g01 (geometry) ---

Geom Title=2003 WVU SAMB 3 Meter DEM
Program Version=4.10

River Reach=PNTRSRN         ,Main
Reach XY= 30
     1666490.782      647627.955     1666096.332      647194.637
     1665730.582      646958.164     1665612.825      646556.617
     1665653.896      646243.527     1665525.151      645938.561
     1665190.788      645532.589     1665150.858      645259.586
     1665006.326      645210.541     1665079.538      645061.617
     1665067.686      644929.012     1664751.737      644629.696
     1664435.741       644635.61     1663975.672      644337.867
     1663809.873      644119.985     1663809.873      643777.971
     1663593.835      643487.183     1663524.173      643238.702
     1663374.977      642961.999     1663092.709      642698.219
     1663009.029      642535.314     1662529.631      642493.257
     1662185.143      642802.828     1661847.817      642995.276
      1661731.15      642858.123     1661713.519      642679.881
     1661512.013       642638.15     1661469.056      642752.704
     1661281.227      642492.381       1661166.8      642449.274

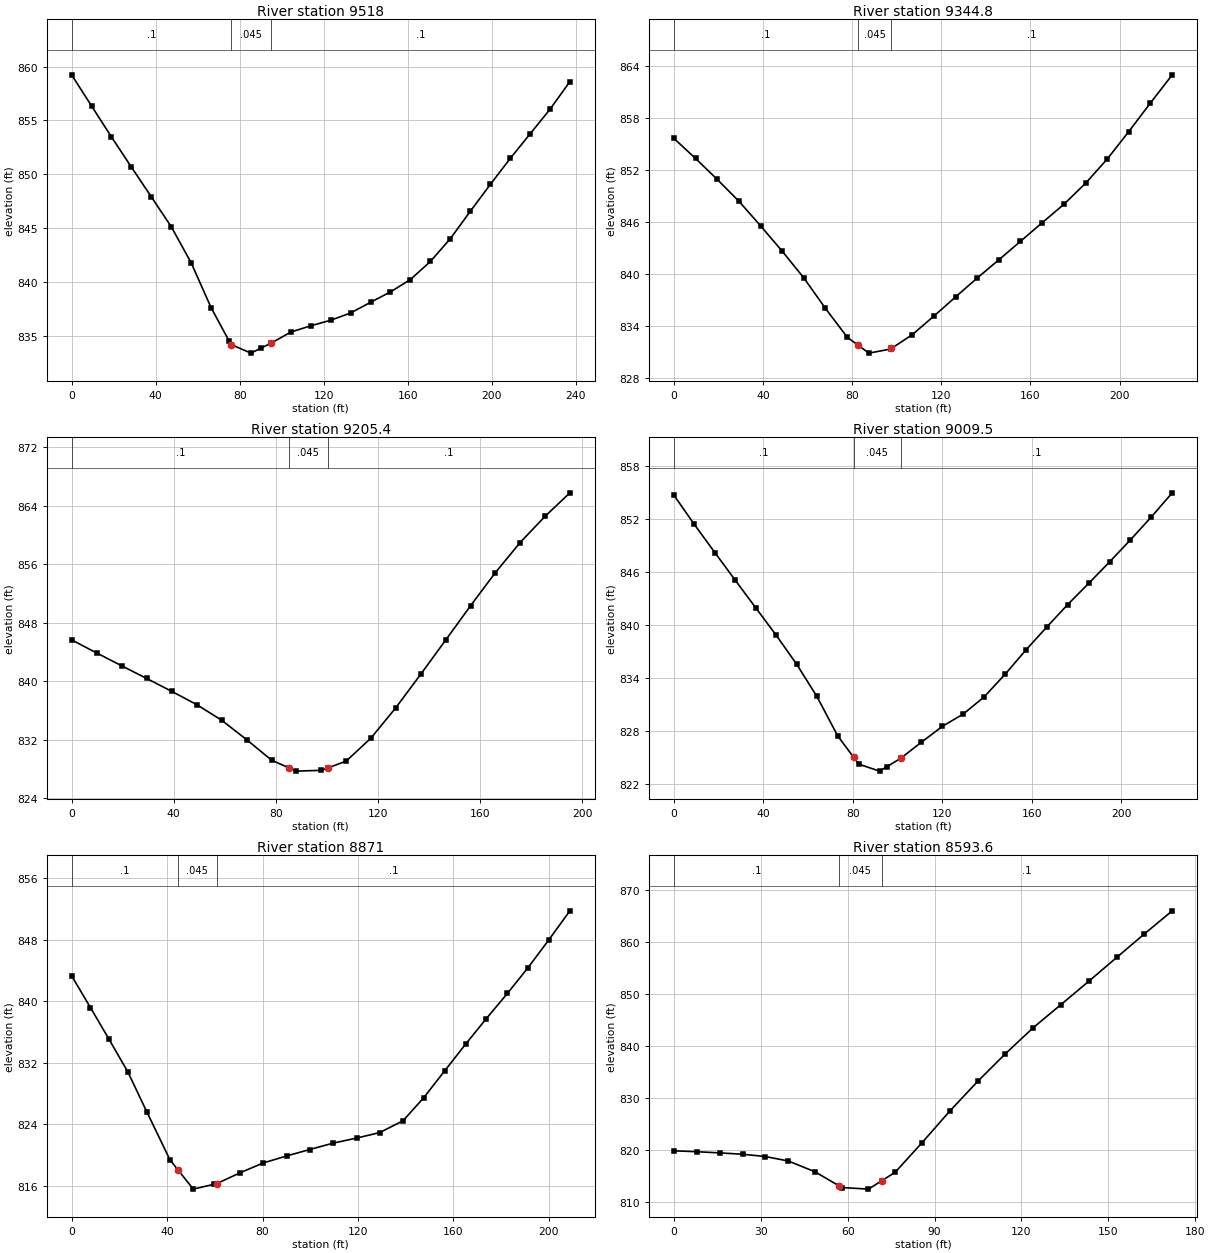
Type RM Length L Ch R = 1 ,9518    ,172.7,173.2,173.4
XS GIS Cut Line= 2
     1666541.615      647563.973     1666368.004      647725.649
#Sta/Elev= 28
       0  859.24     9.5  856.35      19  853.46    28.5  850.66      38  847.89
    47.4  845.14    56.9  841.78    66.4  837.61      75   834.5    75.9  834.18
    85.4  833.38      90  833.83    94.9   834.3   104.4  835.34   113.9  835.92
   123.4  836.44   132.8  837.11   142.3   838.1   151.8  839.07   161.3  840.22
   170.8   841.9   180.3  844.02   189.8  846.56   199.3  849.05   208.8  851.47
   218.2  853.74   227.7  856.03   237.2  858.61
#Mann= 3 , 0 , 0
       0      .1       0    75.9    .045       0    94.9      .1       0
Bank Sta=75.9,94.9
XS Rating Curve= 0 ,0
Exp/Cntr=0.3,0.1

Type RM Length L Ch R = 1 ,9344.8  ,138.5,139.4,140.1
XS GIS Cut Line= 2
     1666422.257      647441.361     1666256.242        647591.1
#Sta/Elev= 26
       0  855.63     9.7  853.32    19.4  850.91    29.2  848.37    38.9  845.54
    48.6  842.61    58.3  839.53      68  836.01    77.8  832.68    82.6  831.77
    87.5  830.85    97.2  831.32    97.6  831.39   106.9  832.97   116.6  835.11
   126.4  837.34   136.1  839.52   145.8  841.62   155.5  843.75   165.2  845.89
     175  848.03   184.7  850.45   194.4  853.24   204.1  856.42   213.8  859.71
   223.6  862.97
#Mann= 3 , 0 , 0
       0      .1       0    82.6    .045       0    97.6      .1       0
Bank Sta=82.6,97.6
XS Rating Curve= 0 ,0
Exp/Cntr=0.3,0.1

Type RM Length L Ch R = 1 ,9205.4  ,197.7,196,193.5
XS GIS Cut Line= 3
     1666327.856      647358.895     1666276.858      647388.192
     1666172.692      647476.083
#Sta/Elev= 23
       0  845.65     9.8  843.86    19.6   842.1    29.4  840.36    39.2   838.6
      49  836.78    58.8  834.63    68.6  831.96    78.3  829.17    85.2   828.1
      88  827.67    97.8  827.78   100.2  828.09   107.5  829.04   117.2  832.19
     127  836.38   136.7  840.94   146.4  845.59   156.2  850.32   165.9  854.85
   175.6  858.98   185.4  862.58   195.1  865.79
#Mann= 3 , 0 , 0
       0      .1       0    85.2    .045       0   100.2      .1       0
Bank Sta=85.2,100.2
XS Rating Curve= 0 ,0
Exp/Cntr=0.3,0.1

Type RM Length L Ch R = 1 ,9009.5  ,138.1,138.5,138.9
XS GIS Cut Line= 3
     1666213.924      647193.965     1666165.096      647235.197
     1666053.334      647348.045
#Sta/Elev= 27
       0  854.71     9.1   851.4    18.3  848.21    27.4  845.08    36.5  841.98
    45.6  838.89    54.8  835.59    63.9  831.92    73.2  827.46    80.3  825.04
    82.6  824.26    91.9  823.47    95.3  823.99   101.3  824.91   110.6  826.74
     120  828.54   129.3  829.93   138.6  831.86     148  834.43   157.3  837.18
   166.7   839.8     176  842.33   185.4  844.73   194.7  847.15     204  849.64
   213.4  852.25   222.7  854.97
#Mann= 3 , 0 , 0
       0      .1       0    80.3    .045       0   101.3      .1       0
Bank Sta=80.3,101.3
XS Rating Curve= 0 ,0
Exp/Cntr=0.3,0.1

Type RM Length L Ch R = 1 ,8871    ,285.9,277.4,268.1
XS GIS Cut Line= 4
     1666085.886      647119.095     1666064.185      647141.881
     1665987.145      647216.751     1665956.763      647279.685
#Sta/Elev= 26
       0  843.33     7.9   839.2    15.7  835.07    23.6  830.82    31.5  825.66
    41.2  819.42    44.5  818.13      51   815.6    59.5  816.22    60.8  816.31
    70.5  817.71    80.3     819    90.1  819.91    99.8  820.75   109.6  821.58
   119.4  822.23   129.1  822.95   138.9  824.49   147.6   827.5   156.4     831
   165.1  834.44   173.8  837.77   182.6  841.03   191.3   844.4     200  848.01
   208.8  851.77
#Mann= 3 , 0 , 0
       0      .1       0    44.5    .045       0    60.8      .1       0
Bank Sta=44.5,60.8
XS Rating Curve= 0 ,0
Exp/Cntr=0.3,0.1

Type RM Length L Ch R = 1 ,8593.6  ,144.9,166.7,188.1
XS GIS Cut Line= 4
     1665828.725      646983.461     1665814.619      647020.354
     1665796.172      647062.671     1665785.322      647148.392
#Sta/Elev= 22
       0  819.82     7.9  819.65    15.8  819.42    23.7  819.16    31.6  818.72
    39.5  817.86    48.7  815.79    56.9  813.11      58  812.75    67.2  812.44
    71.9   814.1    76.4  815.68    85.7  821.39    95.3  827.49   104.9  833.19
   114.5  838.53   124.1  843.54   133.7     848   143.3  852.49   152.9  857.06
   162.5  861.61   172.1  866.05
#Mann= 3 , 0 , 0
       0      .1       0    56.9    .045       0    71.9      .1       0
Bank Sta=56.9,71.9
XS Rating Curve= 0 ,0
Exp/Cntr=0.3,0.1

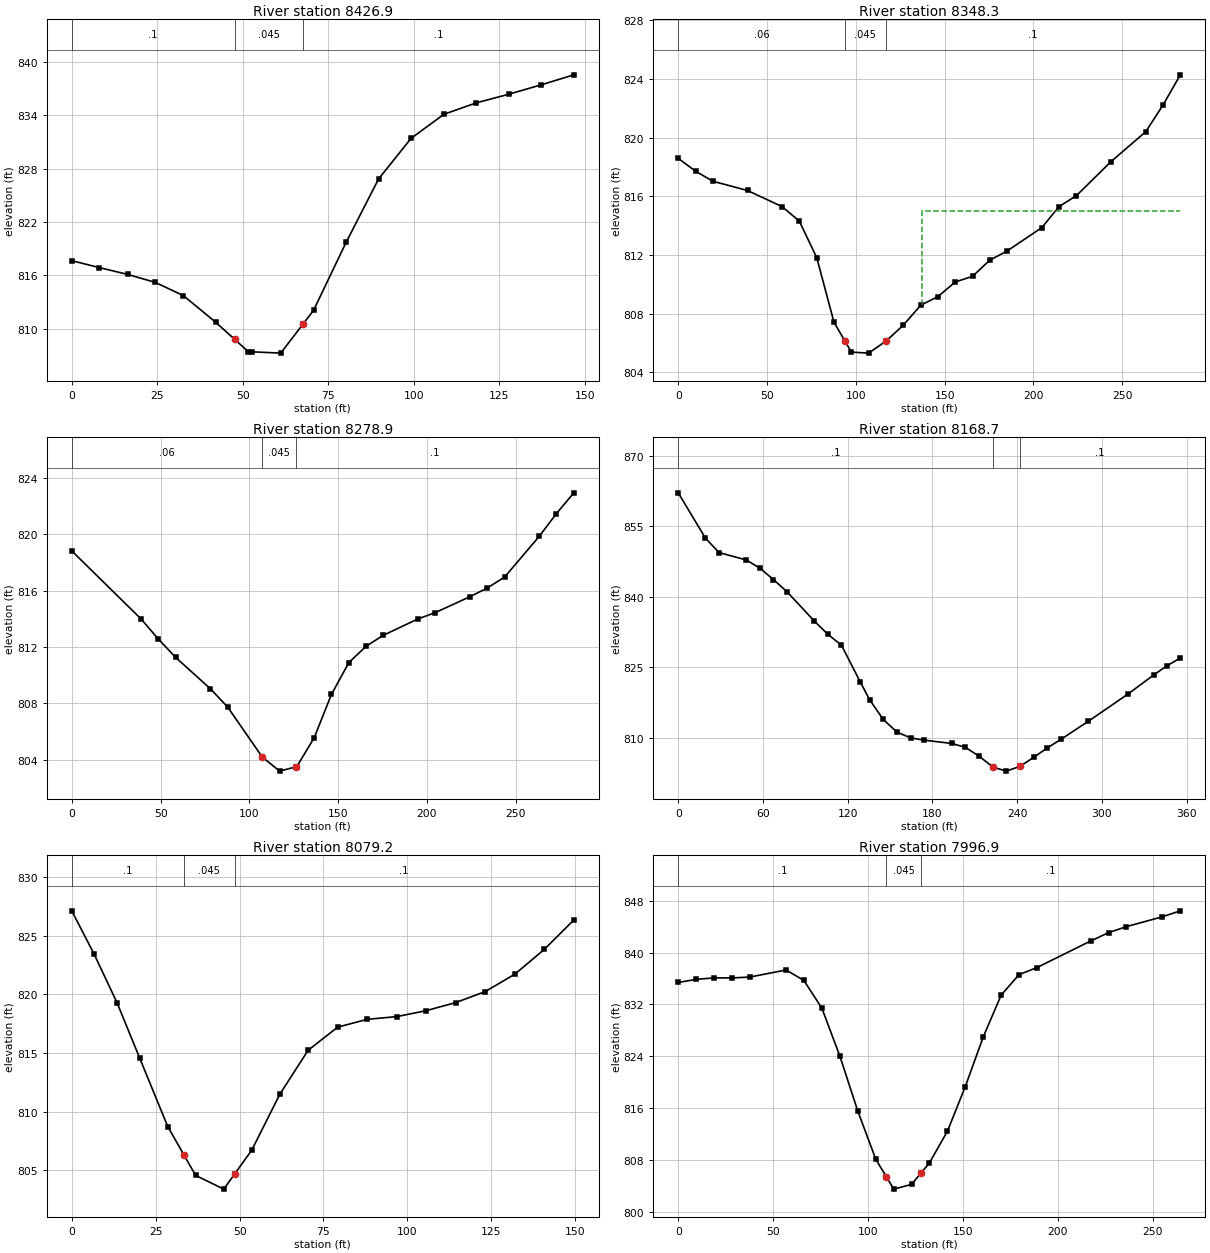
Type RM Length L Ch R = 1 ,8426.9  ,60.8,78.6,95.8
XS GIS Cut Line= 3
     1665770.131      646903.166     1665737.579      646904.251
     1665625.817      646928.123
#Sta/Elev= 20
       0  817.66     8.1  816.88    16.3  816.12    24.4  815.22    32.6  813.74
    42.1  810.73   47.62808.8125    51.6  807.43    52.6  807.41    61.1  807.26
    67.6  810.52    70.7  812.08    80.2  819.71    89.7  826.85    99.2  831.42
   108.8  834.13   118.3  835.42   127.8  836.39   137.3  837.45   146.8  838.57
#Mann= 3 , 0 , 0
       0      .1       0   47.62    .045       0    67.6      .1       0
Bank Sta=47.62,67.6
XS Rating Curve= 0 ,0
Exp/Cntr=0.3,0.1

Type RM Length L Ch R = 1 ,8348.3  ,69.6,69.4,73.7
XS GIS Cut Line= 2
     1665788.577      646881.465     1665541.181      646744.746
#Sta/Elev= 26
       0  818.58     9.8   817.7    19.5  817.02      39  816.39    58.5  815.29
    68.2   814.3      78  811.81    87.7  807.41    93.8  806.15    97.5  805.38
   107.2  805.31     117  806.13   126.7  807.21   136.5  808.57   146.2  809.16
     156  810.16   165.7  810.54   175.4  811.64   185.2  812.27   204.7  813.86
   214.4  815.29   224.2  816.04   243.7  818.36   263.2  820.39   272.9   822.2
   282.7  824.27
#Mann= 3 , 0 , 0
       0     .06       0    93.8    .045       0     117      .1       0
#XS Ineff= 2 , 0
       0                     137       0     815
Permanent Ineff=
       F       F
Bank Sta=93.8,117
XS Rating Curve= 0 ,0
Exp/Cntr=0.3,0.1

Type RM Length L Ch R = 1 ,8278.9  ,124.7,110.3,92
XS GIS Cut Line= 2
     1665801.598      646820.701     1665554.202      646683.982
#Sta/Elev= 23
       0  818.83      39     814    48.7  812.58    58.5  811.27      78  809.05
    87.7  807.76   107.2  804.21     117   803.2   126.4  803.51   126.7  803.52
   136.5  805.57   146.2  808.64     156   810.9   165.7  812.06   175.4  812.84
   194.9     814   204.7  814.45   224.2  815.58   233.9  816.19   243.7  816.97
   263.2  819.86   272.9  821.48   282.7  822.95
#Mann= 3 , 0 , 0
       0     .06       0   107.2    .045       0   126.4      .1       0
Bank Sta=107.2,126.4
XS Rating Curve= 0 ,0
Exp/Cntr=0.3,0.1

Type RM Length L Ch R = 1 ,8168.7  ,96.9,89.5,82.3
XS GIS Cut Line= 5
     1665866.702      646702.428      1665765.79      646646.005
     1665747.344        646653.6     1665583.499      646669.876
      1665528.16      646667.706
#Sta/Elev= 30
       0  862.15    19.3  852.48    28.9  849.42    48.2  847.84    57.8   846.1
    67.4  843.68    77.1  841.05    96.4  834.82     106     832   115.6  829.68
   128.9  821.86   135.6  818.03   145.2  813.87   154.9  811.16   164.6  809.94
   174.3  809.44   193.7  808.75   203.4  807.92     213  806.04   223.1  803.68
   232.4  802.85   242.1  803.88   251.8  805.79   261.5  807.82   271.2  809.65
   290.5  813.48   318.7  819.31   337.1  823.42   346.4  825.35   355.6  826.95
#Mann= 3 , 0 , 0
       0      .1       0   223.1    .045       0   242.1      .1       0
Bank Sta=223.1,242.1
XS Rating Curve= 0 ,0
Exp/Cntr=0.3,0.1

Type RM Length L Ch R = 1 ,8079.2  ,53.3,82.4,107.9
XS GIS Cut Line= 4
     1665652.943      646562.454     1665636.667       646574.39
     1665590.009      646592.836     1665515.139      646618.878
#Sta/Elev= 21
       0  827.13     6.7  823.41    13.5  819.28    20.2  814.59    28.6  808.72
    33.5  806.26    36.9  804.55    45.3  803.38    48.5  804.66    53.6  806.69
      62  811.48    70.4  815.22    79.2   817.2      88  817.87    96.8   818.1
   105.6  818.61   114.4   819.3   123.2  820.24     132  821.72   140.8  823.84
   149.6  826.35
#Mann= 3 , 0 , 0
       0      .1       0    33.5    .045       0    48.5      .1       0
Bank Sta=33.5,48.5
XS Rating Curve= 0 ,0
Exp/Cntr=0.3,0.1

Type RM Length L Ch R = 1 ,7996.9  ,222.8,219.3,222.1
XS GIS Cut Line= 3
     1665705.027      646585.241     1665624.731      646504.946
     1665508.629      646408.374
#Sta/Elev= 27
       0  835.39     9.5  835.87    18.9   836.1    28.4  836.09    37.8  836.23
    56.8  837.32    66.2  835.71    75.7  831.42    85.2  824.01    94.6  815.56
   104.1  808.11  109.74805.3652   113.6  803.49     123  804.23   128.1  806.03
   132.4  807.55   141.9  812.45   151.3  819.33   160.8  827.03   170.2  833.45
   179.6   836.6   189.1   837.7   217.4   841.8   226.8  843.08   236.2  844.01
   255.1  845.53   264.6  846.45
#Mann= 3 , 0 , 0
       0      .1       0  109.74    .045       0   128.1      .1       0
Bank Sta=109.74,128.1
XS Rating Curve= 0 ,0
Exp/Cntr=0.3,0.1

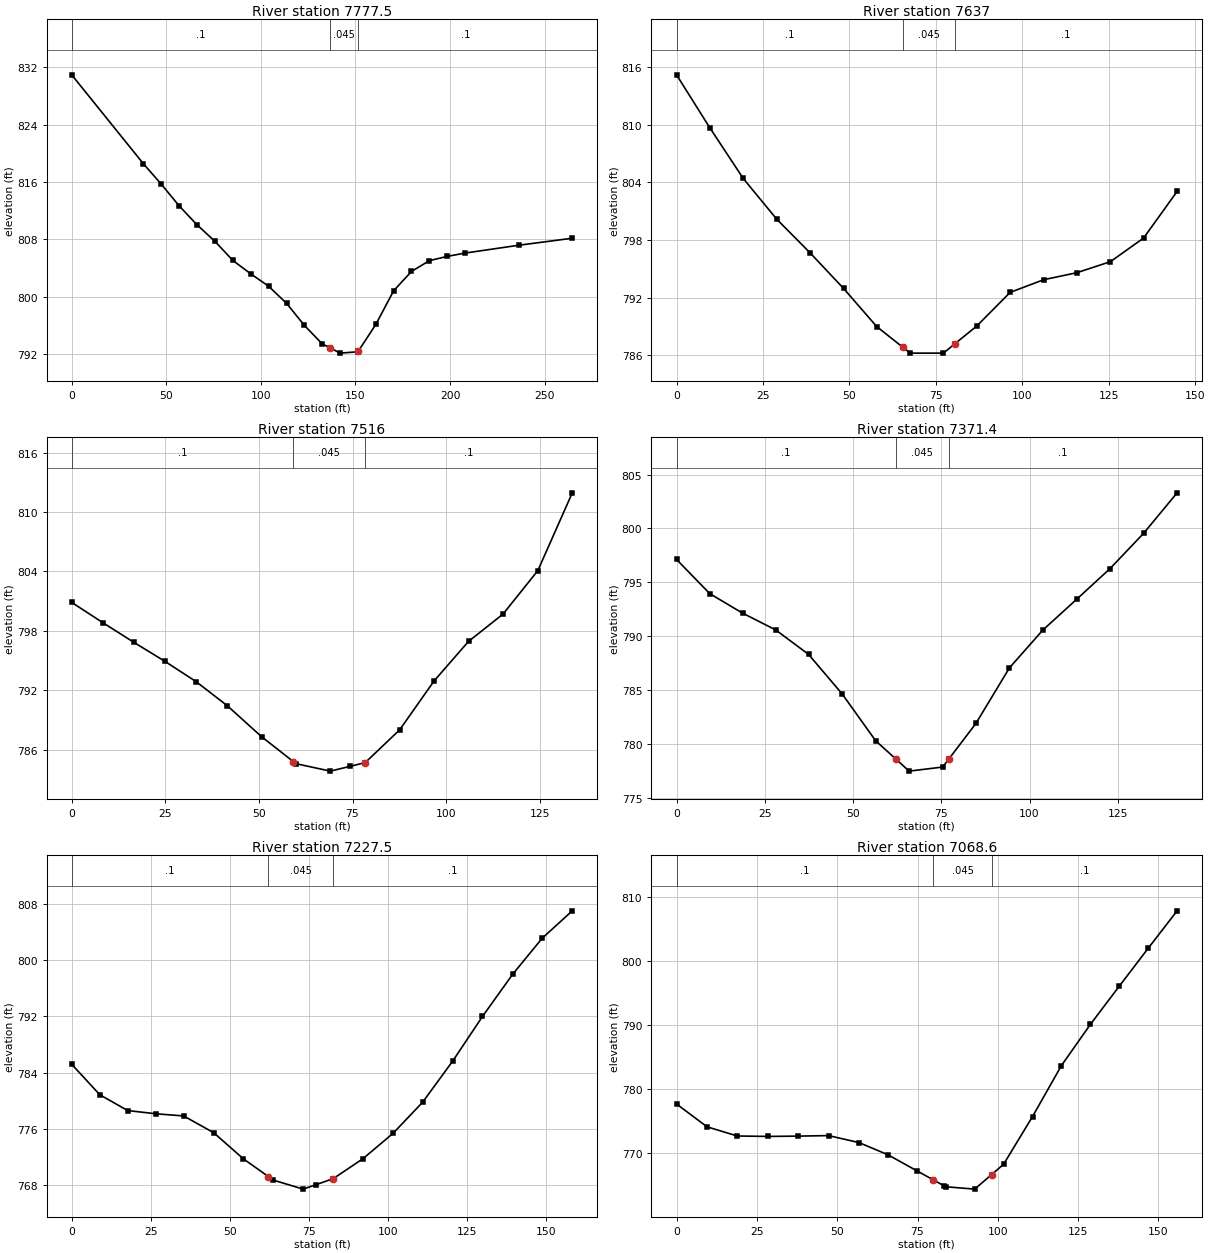
Type RM Length L Ch R = 1 ,7777.5  ,165.9,140.5,110.5
XS GIS Cut Line= 3
     1665762.535      646385.588      1665682.24      646305.293
     1665566.138      646208.722
#Sta/Elev= 24
       0  830.93    37.8  818.57    47.3  815.71    56.8  812.67    66.2  810.04
    75.7  807.73    85.2  805.06    94.6  803.21   104.1  801.47   113.6  799.08
     123  796.01   132.4  793.45   136.5  792.89   141.9  792.15   151.3  792.34
   151.5  792.42   160.8  796.17   170.2  800.85   179.6  803.53   189.1  805.04
   198.5  805.63   207.9  806.09   236.2  807.18   264.6  808.16
#Mann= 3 , 0 , 0
       0      .1       0   136.5    .045       0   151.5      .1       0
Bank Sta=136.5,151.5
XS Rating Curve= 0 ,0
Exp/Cntr=0.3,0.1

Type RM Length L Ch R = 1 ,7637    ,121.4,121.1,120.5
XS GIS Cut Line= 2
     1665681.155      646125.171     1665548.777      646183.765
#Sta/Elev= 18
       0  815.21     9.6  809.71    19.3  804.41      29  800.16    38.6  796.67
    48.3  792.96    57.9  788.98    65.5  786.81    67.6  786.21    77.2  786.21
    80.5  787.18    86.9  789.05    96.5  792.54   106.2  793.86   115.8  794.59
   125.5  795.74   135.1   798.2   144.8  803.06
#Mann= 3 , 0 , 0
       0      .1       0    65.5    .045       0    80.5      .1       0
Bank Sta=65.5,80.5
XS Rating Curve= 0 ,0
Exp/Cntr=0.3,0.1

Type RM Length L Ch R = 1 ,7516    ,145.7,144.6,143.4
XS GIS Cut Line= 3
     1665621.476       646032.94     1665580.244      646037.281
     1665496.693      646076.343
#Sta/Elev= 18
       0  800.87     8.3  798.83    16.6  796.84    24.9  794.92    33.2  792.88
    41.5  790.46    50.7  787.32    59.2   784.8    59.9  784.59    69.1  783.84
    74.2  784.31    78.4   784.7    87.6  788.01    96.8  792.95     106  796.94
   115.2  799.69   124.5  804.08   133.7  811.93
#Mann= 3 , 0 , 0
       0      .1       0    59.2    .045       0    78.4      .1       0
Bank Sta=59.2,78.4
XS Rating Curve= 0 ,0
Exp/Cntr=0.3,0.1

Type RM Length L Ch R = 1 ,7371.4  ,155.4,143.9,131.4
XS GIS Cut Line= 3
     1665572.648      645887.541     1665536.841      645898.392
      1665444.61       645947.22
#Sta/Elev= 18
       0  797.12     9.4  793.95    18.7  792.14    28.1  790.58    37.4  788.31
    46.9  784.65    56.4   780.3    62.1  778.61    65.9  777.48    75.4  777.86
    77.1  778.59    84.8   781.9    94.3  787.06   103.8  790.58   113.3  793.41
   122.8  796.27   132.3  799.54   141.8   803.3
#Mann= 3 , 0 , 0
       0      .1       0    62.1    .045       0    77.1      .1       0
Bank Sta=62.1,77.1
XS Rating Curve= 0 ,0
Exp/Cntr=0.3,0.1

Type RM Length L Ch R = 1 ,7227.5  ,148.3,158.8,168.5
XS GIS Cut Line= 3
     1665459.801      645748.652     1665437.014      645775.779
      1665371.91      645879.946
#Sta/Elev= 20
       0  785.18     8.9  780.83    17.7  778.58    26.6  778.12    35.4  777.81
    44.9  775.42    54.3  771.69    62.2  769.16    63.8  768.65    73.2  767.37
    77.2     768    82.7  768.86    92.1  771.71   101.6  775.32     111  779.78
   120.5  785.65   129.9     792   139.4  797.99   148.8  803.17   158.3  807.07
#Mann= 3 , 0 , 0
       0      .1       0    62.2    .045       0    82.7      .1       0
Bank Sta=62.2,82.7
XS Rating Curve= 0 ,0
Exp/Cntr=0.3,0.1

Type RM Length L Ch R = 1 ,7068.6  ,180.2,181.2,181.9
XS GIS Cut Line= 3
      1665371.91      645668.357     1665321.997      645695.484
     1665238.447      645748.652
#Sta/Elev= 21
       0   777.7     9.5  774.14    18.9  772.71    28.4  772.64    37.9  772.69
    47.3  772.77    56.8  771.68    65.8  769.78    74.8  767.28   79.93765.8585
    83.1  764.98    83.8  764.79    92.8  764.42    98.1   766.7   101.8   768.3
   110.8  775.74   119.8   783.7   128.8  790.11   137.8  796.08   146.8  801.99
   155.8  807.83
#Mann= 3 , 0 , 0
       0      .1       0   79.93    .045       0    98.1      .1       0
Bank Sta=79.93,98.1
XS Rating Curve= 0 ,0
Exp/Cntr=0.3,0.1

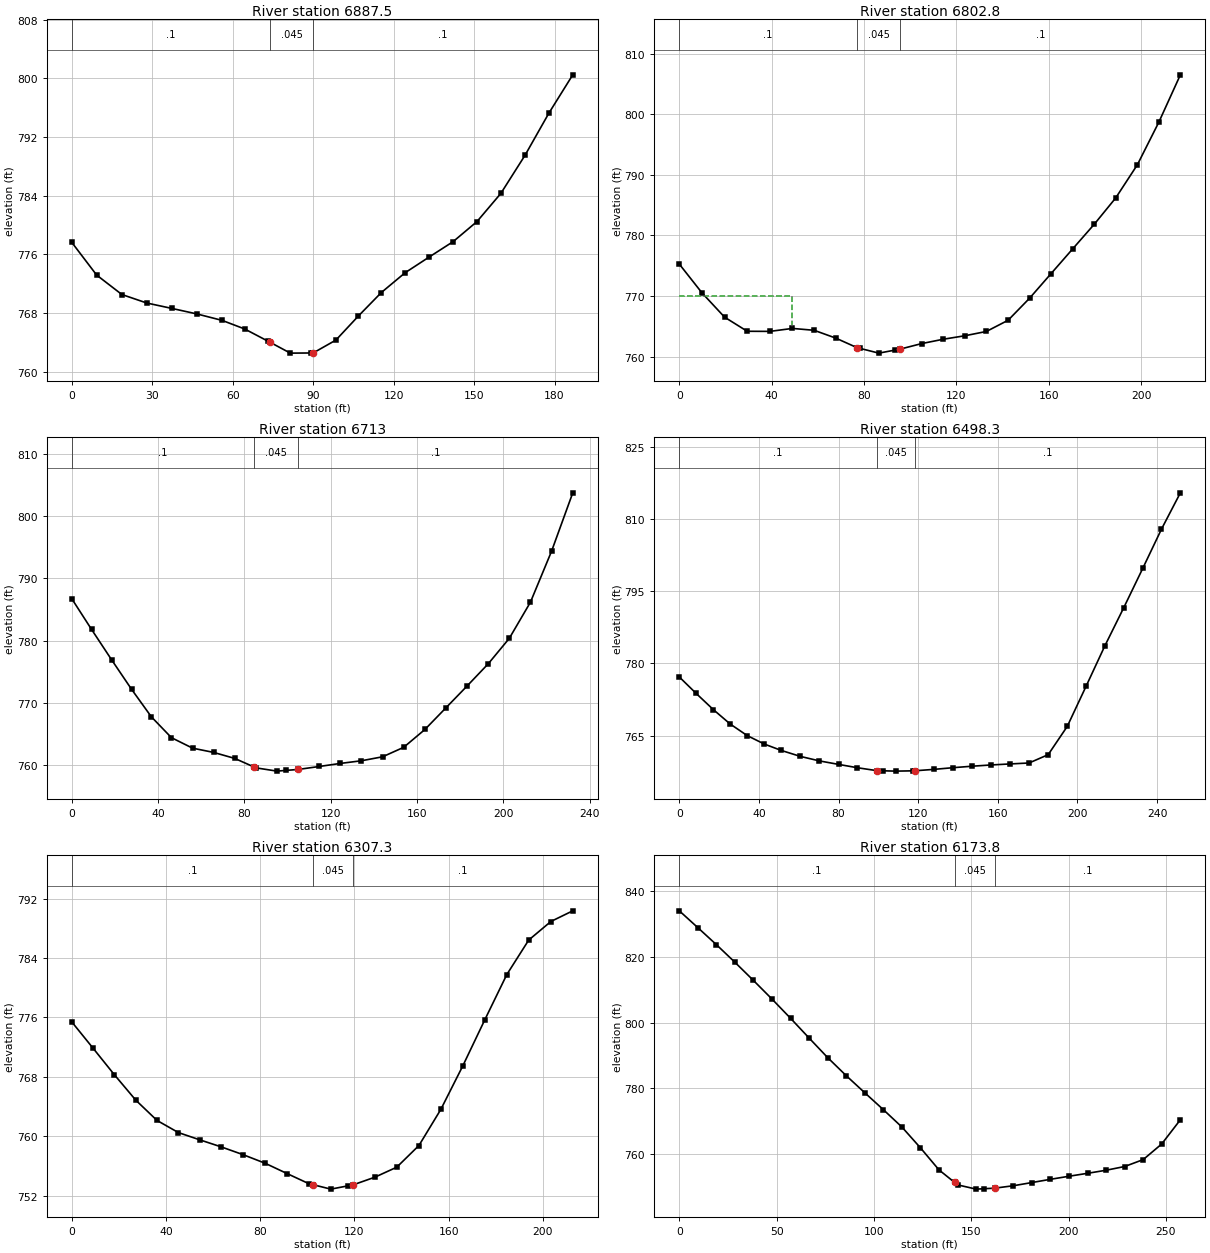
Type RM Length L Ch R = 1 ,6887.5  ,84.7,84.7,84.5
XS GIS Cut Line= 4
      1665290.53      645525.128     1665236.277      645539.234
     1665185.278      645569.616      1665136.45      645621.699
#Sta/Elev= 24
       0  777.65     9.3  773.18    18.7  770.53      28  769.37    37.4  768.63
    46.7  767.88    56.1     767    64.5  765.83      73   764.2    74.1  763.99
    81.5  762.54    89.1  762.56      90  762.56    98.5  764.32   106.9  767.61
   115.4  770.79   124.3   773.5   133.3  775.65   142.2  777.74   151.1  780.48
     160  784.32     169  789.51   177.9  795.26   186.8  800.48
#Mann= 3 , 0 , 0
       0      .1       0    74.1    .045       0      90      .1       0
Bank Sta=74.1,90
XS Rating Curve= 0 ,0
Exp/Cntr=0.3,0.1

Type RM Length L Ch R = 1 ,6802.8  ,88.5,89.8,90.6
XS GIS Cut Line= 3
     1665256.893      645439.407      1665213.49      645462.194
     1665065.921      645542.489
#Sta/Elev= 26
       0  775.27     9.8  770.53    19.6  766.51    29.4  764.18    39.2  764.16
      49  764.65    58.4  764.34    67.7  763.06      77  761.47    78.4  761.34
    86.4  760.57    93.4  761.07    95.7  761.24     105  762.15   114.4  762.87
   123.7  763.44     133  764.15   142.4     766   151.7  769.64     161   773.7
   170.4   777.8   179.7  781.85     189   786.2   198.4  791.69   207.7  798.73
     217  806.53
#Mann= 3 , 0 , 0
       0      .1       0      77    .045       0    95.7      .1       0
#XS Ineff= 2 , 0
       0      49     770               0
Permanent Ineff=
       F       F
Bank Sta=77,95.7
XS Rating Curve= 0 ,0
Exp/Cntr=0.3,0.1

Type RM Length L Ch R = 1 ,6713    ,195.4,214.7,218.7
XS GIS Cut Line= 3
     1665237.362      645355.857     1665195.044      645374.303
     1665031.198      645462.194
#Sta/Elev= 27
       0  786.75     9.2  781.78    18.5  776.88    27.7  772.15    36.9   767.7
    46.2  764.34      56  762.65    65.7  761.97    75.5     761    84.3  759.64
    85.3  759.48    95.1  758.95    99.3  759.07   104.9  759.22   114.7   759.7
   124.4  760.19   134.2  760.62     144  761.26   153.8  762.79   163.6  765.66
   173.4  769.17   183.2  772.69     193  776.27   202.7  780.35   212.5  786.18
   222.3  794.41   232.1   803.8
#Mann= 3 , 0 , 0
       0      .1       0    84.3    .045       0   104.9      .1       0
Bank Sta=84.3,104.9
XS Rating Curve= 0 ,0
Exp/Cntr=0.3,0.1

Type RM Length L Ch R = 1 ,6498.3  ,197.1,191,197.1
XS GIS Cut Line= 4
     1665175.513      645184.416      1665134.28      645214.798
     1665006.242      645279.902     1664954.159      645302.689
#Sta/Elev= 30
       0  777.17     8.5  773.74    17.1  770.39    25.6  767.39    34.1     765
    42.7  763.24    51.2  761.92    60.8  760.68    70.4  759.74      80  759.02
    89.5  758.32    99.1  757.73   102.2  757.69   108.7  757.62   117.2  757.68
   118.2  757.69   127.8  757.98   137.4  758.33     147  758.64   156.6   758.9
   166.1  759.11   175.7  759.31   185.3  761.04   194.9  766.92   204.3  775.21
   213.8  783.66   223.3  791.59   232.8  799.72   242.2  807.86   251.7  815.41
#Mann= 3 , 0 , 0
       0      .1       0    99.1    .045       0   118.2      .1       0
Bank Sta=99.1,118.2
XS Rating Curve= 0 ,0
Exp/Cntr=0.3,0.1

Type RM Length L Ch R = 1 ,6307.3  ,135.4,133.5,128.7
XS GIS Cut Line= 3
     1665152.726      645127.993     1665089.792      645120.397
     1664941.138      645106.291
#Sta/Elev= 26
       0  775.41     9.1  771.84    18.1  768.28    27.2  764.85    36.2  762.12
    45.3  760.48    54.3  759.51    63.4  758.56    72.7  757.51    82.1  756.35
    91.4  754.96   100.7  753.59   102.4  753.46     110  752.86   117.4  753.31
   119.4  753.43   128.7  754.47     138  755.82   147.4  758.74   156.7  763.61
     166  769.46   175.4  775.71   184.7  781.78     194  786.43   203.4  788.93
   212.7  790.37
#Mann= 3 , 0 , 0
       0      .1       0   102.4    .045       0   119.4      .1       0
Bank Sta=102.4,119.4
XS Rating Curve= 0 ,0
Exp/Cntr=0.3,0.1

Type RM Length L Ch R = 1 ,6173.8  ,188.9,168.9,148.5
XS GIS Cut Line= 2
      1665209.15      645006.465     1664951.988      644996.699
#Sta/Elev= 30
       0  834.03     9.5  828.92    19.1  823.71    28.6  818.36    38.1  812.84
    47.7  807.14    57.2  801.31    66.7  795.32    76.2  789.39    85.8  783.86
    95.3  778.68   104.8  773.56   114.4  768.24   123.9  761.92   133.4  755.23
   141.4  751.43     143  750.67   152.5  749.38   156.4   749.5     162  749.67
   171.6  750.41   181.1  751.38   190.6  752.36   200.2   753.3   209.7  754.19
   219.2  755.12   228.8  756.26   238.3  758.36   247.8   763.1   257.4  770.48
#Mann= 3 , 0 , 0
       0      .1       0   141.4    .045       0     162      .1       0
Bank Sta=141.4,162
XS Rating Curve= 0 ,0
Exp/Cntr=0.3,0.1

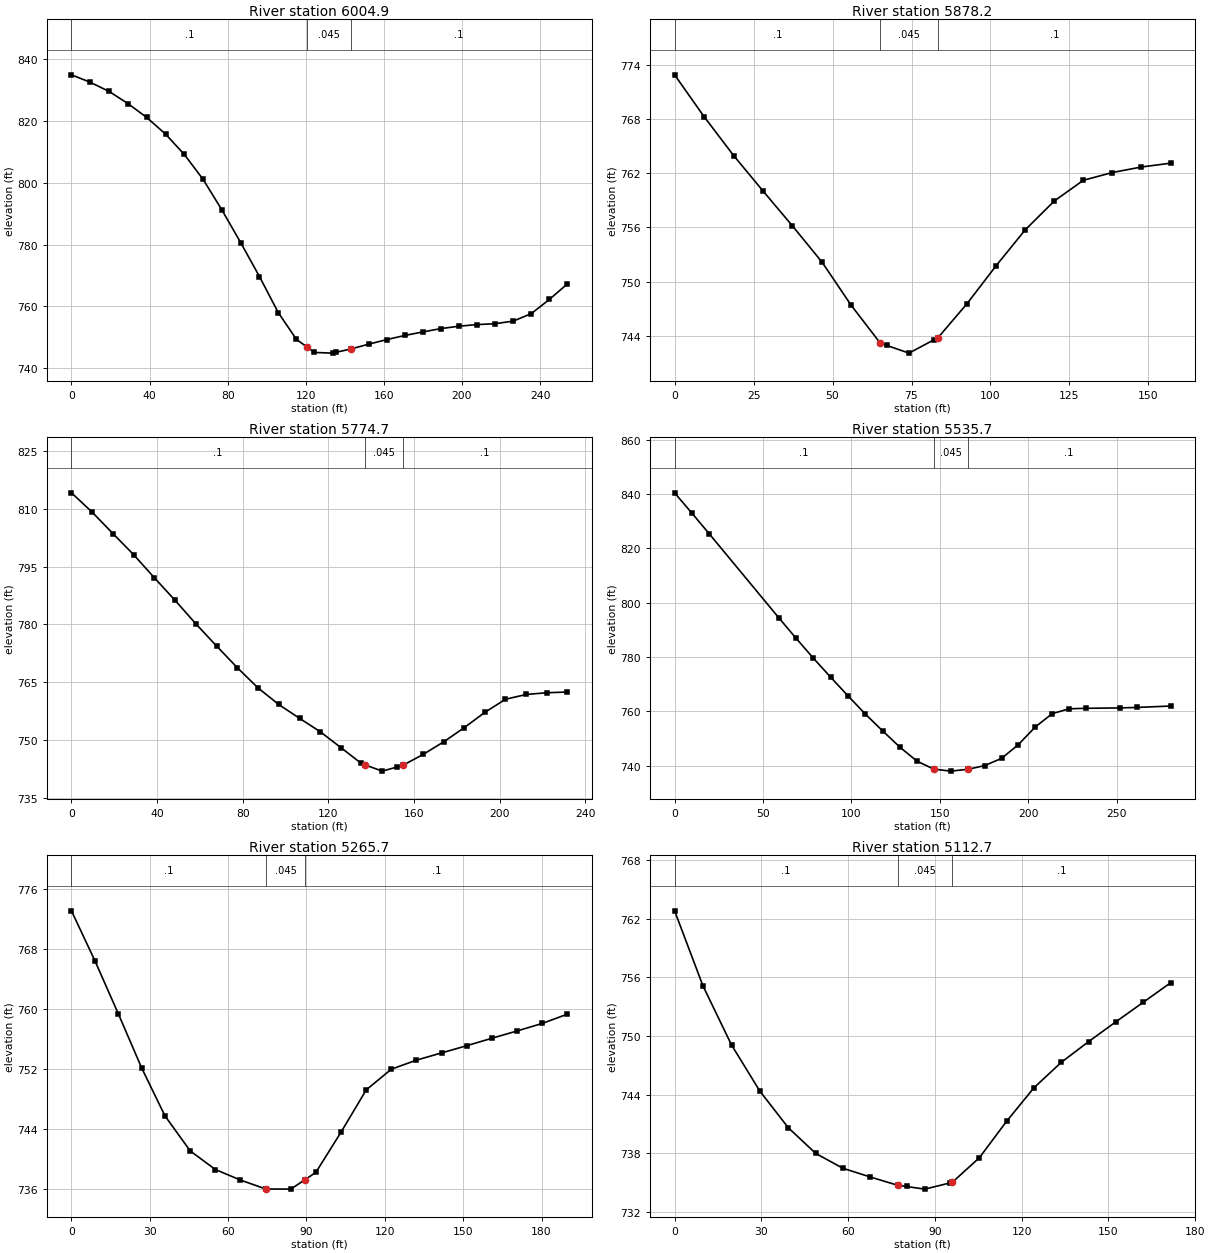
Type RM Length L Ch R = 1 ,6004.9  ,128.8,126.7,124.8
XS GIS Cut Line= 3
     1665089.792        644778.6     1665012.752        644851.3
     1664909.671      644957.637
#Sta/Elev= 30
       0   834.9     9.6   832.5    19.3  829.52    28.9  825.61    38.5  821.14
    48.2  815.72    57.8  809.14    67.4  801.11      77  791.25    86.7   780.6
    96.3  769.64   105.9  758.03   115.2  749.36   120.7  746.82   124.4  745.11
   133.7  744.89   135.7  745.18     143  746.22   152.2  747.78   161.5  749.27
   170.7   750.6     180  751.75   189.2  752.82   198.5   753.6   207.7  754.12
     217  754.41   226.3  755.25   235.5  757.66   244.8  762.26     254  767.28
#Mann= 3 , 0 , 0
       0      .1       0   120.7    .045       0     143      .1       0
Bank Sta=120.7,143
XS Rating Curve= 0 ,0
Exp/Cntr=0.3,0.1

Type RM Length L Ch R = 1 ,5878.2  ,104,103.5,103.1
XS GIS Cut Line= 3
     1664943.308      644730.857     1664916.181      644768.835
     1664846.737      644854.555
#Sta/Elev= 20
       0  772.87     9.3  768.26    18.7  763.94      28  760.02    37.3  756.17
    46.7  752.15    55.9  747.39    65.1  743.21    67.2  742.95    74.2   742.1
    82.2  743.59    83.4  743.81    92.6  747.58   101.8  751.77     111  755.73
   120.2  758.92   129.4  761.21   138.6  762.07   147.8  762.68     157   763.1
#Mann= 3 , 0 , 0
       0      .1       0    65.1    .045       0    83.4      .1       0
Bank Sta=65.1,83.4
XS Rating Curve= 0 ,0
Exp/Cntr=0.3,0.1

Type RM Length L Ch R = 1 ,5774.7  ,253,239.1,222.2
XS GIS Cut Line= 3
      1664898.82      644594.138     1664836.971       644703.73
     1664770.782      644786.196
#Sta/Elev= 27
       0  814.17     9.7  809.14    19.4  803.57      29  798.14    38.7  792.13
    48.4  786.26    58.1  780.16    67.8  774.39    77.4  768.82    87.1  763.55
    96.8  759.24   106.5  755.65   116.2  752.16   125.8  748.06   135.4  743.92
     137  743.59   145.1  741.94     152     743   154.7  743.42   164.3   746.3
   173.9  749.56   183.5  753.25   193.1  757.21   202.7  760.59   212.4  761.84
     222  762.28   231.6  762.47
#Mann= 3 , 0 , 0
       0      .1       0     137    .045       0   154.7      .1       0
Bank Sta=137,154.7
XS Rating Curve= 0 ,0
Exp/Cntr=0.3,0.1

Type RM Length L Ch R = 1 ,5535.7  ,258.5,270,281.8
XS GIS Cut Line= 3
     1664651.424      644487.802     1664639.488      644614.755
     1664640.573      644767.749
#Sta/Elev= 25
       0  840.49     9.8     833    19.6  825.39    58.8  794.57    68.7  786.92
    78.5  779.58    88.3  772.56    98.1   765.7   107.9     759   117.7  752.79
   127.5  746.77   137.1  741.67   146.6  738.72   156.2  737.99   165.8  738.65
   175.3  740.02   184.9  742.67   194.4  747.73     204  754.25   213.6  759.16
   223.1  760.95   232.7  761.13   251.8  761.27   261.4  761.45   280.5  761.96
#Mann= 3 , 0 , 0
       0      .1       0   146.6    .045       0   165.8      .1       0
Bank Sta=146.6,165.8
XS Rating Curve= 0 ,0
Exp/Cntr=0.3,0.1

Type RM Length L Ch R = 1 ,5265.7  ,153.1,153,152.7
XS GIS Cut Line= 3
      1664423.56       644534.46     1664402.943      644563.756
     1664325.903       644697.22
#Sta/Elev= 23
       0  773.09       9  766.41    17.9  759.38    26.9   752.1    35.8  745.72
    45.5  741.03    55.1  738.56    64.7  737.15    74.4  735.96    74.5  735.96
      84  735.94    89.5  737.22    93.6  738.18   103.2  743.53   112.9   749.2
   122.5  751.95   132.1  753.16   141.8  754.13   151.4  755.09     161  756.08
   170.7  757.06   180.3  758.06   189.9   759.3
#Mann= 3 , 0 , 0
       0      .1       0    74.4    .045       0    89.5      .1       0
Bank Sta=74.4,89.5
XS Rating Curve= 0 ,0
Exp/Cntr=0.3,0.1

Type RM Length L Ch R = 1 ,5112.7  ,153.7,157.4,161.2
XS GIS Cut Line= 3
     1664292.266       644463.93      1664267.31      644494.312
     1664202.205      644609.329
#Sta/Elev= 21
       0  762.83     9.8  755.14    19.7  749.07    29.5  744.34    39.3   740.6
    48.8  737.96    58.2  736.44    67.6  735.55    77.1   734.7    80.2  734.57
    86.5   734.3    95.2  734.93      96  734.99   105.4  737.52   114.8  741.25
   124.3   744.7   133.7  747.29   143.2  749.43   152.6  751.45     162  753.44
   171.5  755.45
#Mann= 3 , 0 , 0
       0      .1       0    77.1    .045       0      96      .1       0
Bank Sta=77.1,96
XS Rating Curve= 0 ,0
Exp/Cntr=0.3,0.1

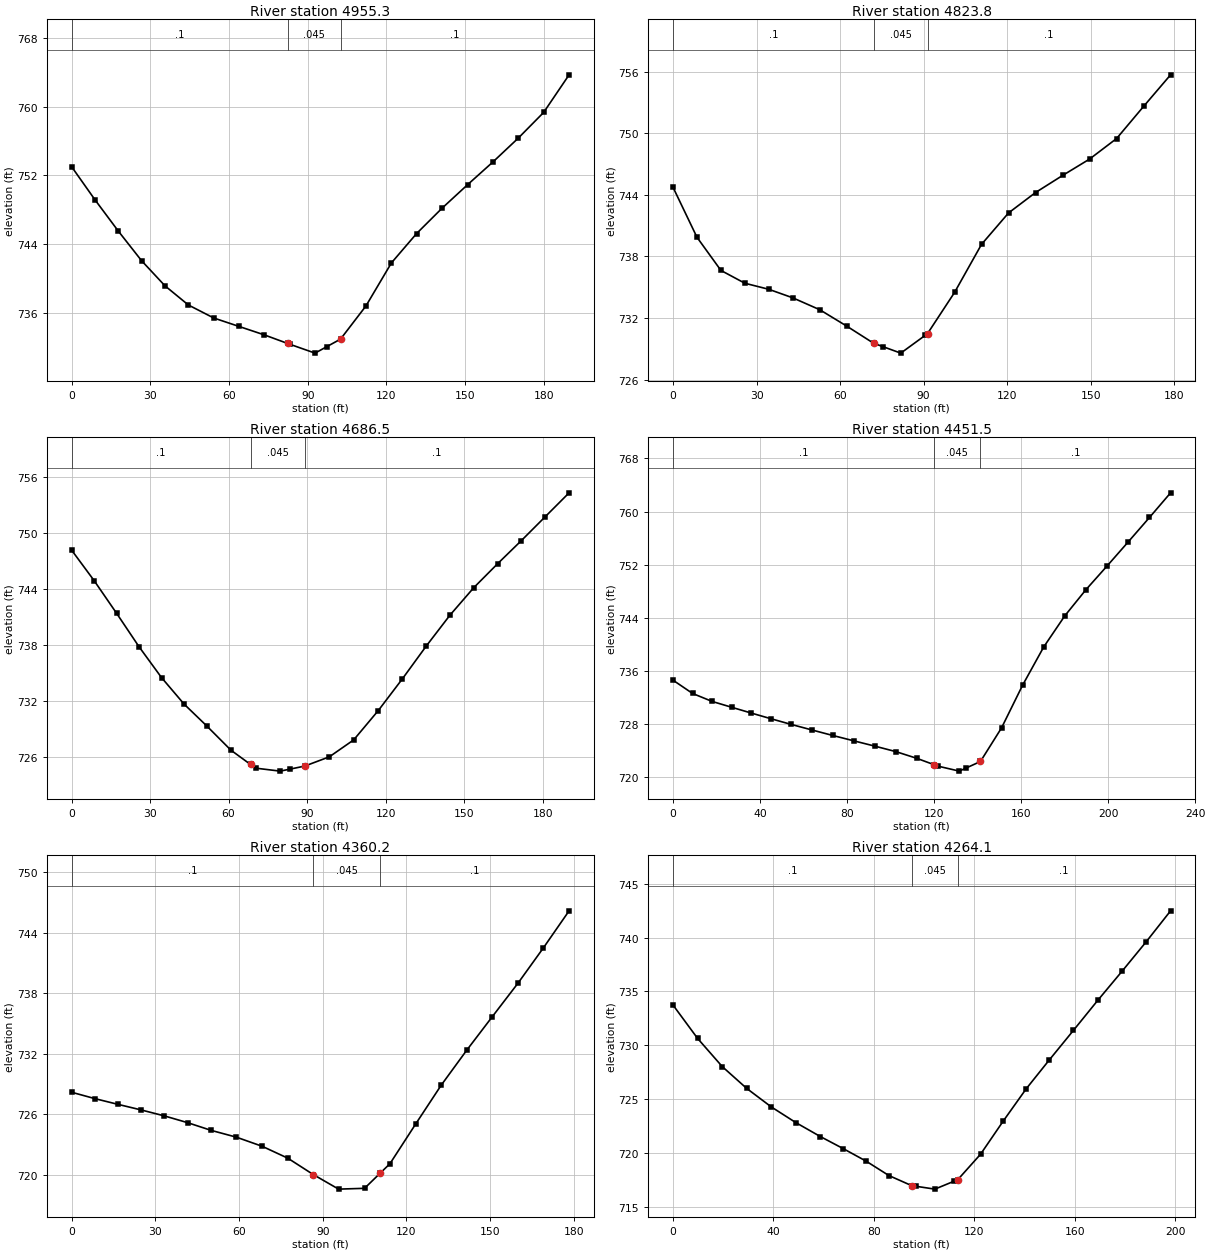
Type RM Length L Ch R = 1 ,4955.3  ,131.1,131.4,131.3
XS GIS Cut Line= 3
     1664169.653       644386.89     1664138.186      644418.357
      1664047.04      644531.204
#Sta/Elev= 23
       0  753.03     8.9  749.18    17.8  745.53    26.7  742.07    35.6  739.15
    44.5  736.92    54.2   735.4    63.8  734.42    73.5  733.43    82.3  732.44
    83.2  732.34    92.8  731.31    97.3  732.07   102.5  732.94   112.2  736.81
   121.9  741.82   131.5  745.24   141.2  748.19   150.9  750.92   160.6  753.58
   170.2  756.34   179.9  759.34   189.6  763.72
#Mann= 3 , 0 , 0
       0      .1       0    82.3    .045       0   102.5      .1       0
Bank Sta=82.3,102.5
XS Rating Curve= 0 ,0
Exp/Cntr=0.3,0.1

Type RM Length L Ch R = 1 ,4823.8  ,129.5,137.4,145.4
XS GIS Cut Line= 3
     1664064.402      644308.765      1664034.02      644339.147
     1663948.299      644444.399
#Sta/Elev= 22
       0  744.73     8.6  739.86    17.2  736.63    25.8  735.38    34.4  734.79
      43  733.96    52.7   732.8    62.4   731.2      72  729.54    75.5  729.19
    81.8  728.57    90.5  730.29    91.4  730.47   101.1  734.48   110.8  739.17
   120.5  742.23   130.2  744.22   139.9  745.88   149.6  747.48   159.3  749.48
     169  752.61   178.7  755.69
#Mann= 3 , 0 , 0
       0      .1       0      72    .045       0    91.4      .1       0
Bank Sta=72,91.4
XS Rating Curve= 0 ,0
Exp/Cntr=0.3,0.1

Type RM Length L Ch R = 1 ,4686.5  ,221.7,234.9,247.3
XS GIS Cut Line= 4
     1664003.638      644216.534      1663959.15      644242.576
     1663902.726      644276.213     1663850.643      644327.211
#Sta/Elev= 24
       0  748.14     8.6  744.88    17.2  741.38    25.8  737.79    34.4  734.49
      43  731.66    51.6  729.34    60.9  726.73    68.4   725.2    70.3  724.81
    79.7  724.49    83.4   724.7    89.1  725.03    98.5  726.02   107.8  727.83
   117.2  730.97   126.4  734.36   135.5  737.86   144.6  741.18   153.7  744.12
   162.8  746.68   171.9  749.16     181  751.71   190.1  754.26
#Mann= 3 , 0 , 0
       0      .1       0    68.4    .045       0    89.1      .1       0
Bank Sta=68.4,89.1
XS Rating Curve= 0 ,0
Exp/Cntr=0.3,0.1

Type RM Length L Ch R = 1 ,4451.5  ,98.7,91.4,83
XS GIS Cut Line= 3
     1663924.428      644066.795     1663872.344      644080.901
     1663697.648       644078.73
#Sta/Elev= 27
       0  734.61       9  732.61      18  731.41      27  730.53      36  729.66
      45  728.81      54  727.98    63.7  727.13    73.4  726.29    83.1  725.48
    92.8  724.68   102.5  723.85   112.2  722.83   119.8  721.91   121.9  721.66
   131.6  720.92   134.8   721.4   141.3  722.37     151  727.43   160.7  733.87
   170.4  739.62   180.1  744.31   189.8  748.24   199.6  751.84   209.3  755.46
     219  759.11   228.7  762.82
#Mann= 3 , 0 , 0
       0      .1       0   119.8    .045       0   141.3      .1       0
Bank Sta=119.8,141.3
XS Rating Curve= 0 ,0
Exp/Cntr=0.3,0.1

Type RM Length L Ch R = 1 ,4360.2  ,88.5,96.1,102.8
XS GIS Cut Line= 3
     1663898.386      643975.649     1663848.473      643973.479
     1663726.945      644014.711
#Sta/Elev= 22
       0  728.16     8.3  727.53    16.6  726.96      25   726.4    33.3  725.81
    41.6  725.14      50  724.38    59.1   723.7    68.3   722.8    77.5  721.62
    86.6     720    95.7  718.55     105  718.63   110.7  720.16   114.1  721.07
   123.3     725   132.5  728.87   141.6  732.32   150.8  735.66     160  738.98
   169.1  742.48   178.3  746.15
#Mann= 3 , 0 , 0
       0      .1       0    86.6    .045       0   110.7      .1       0
Bank Sta=86.6,110.7
XS Rating Curve= 0 ,0
Exp/Cntr=0.3,0.1

Type RM Length L Ch R = 1 ,4264.1  ,231.8,222.2,211.6
XS GIS Cut Line= 4
     1663899.471      643904.034     1663840.877      643900.779
     1663749.731      643900.779     1663704.159      643917.055
#Sta/Elev= 24
       0  733.73     9.8  730.63    19.6  728.02    29.3     726    39.1  724.28
    48.9  722.82    58.7  721.52    67.8   720.4    76.9  719.24      86   717.9
    95.1  716.96    96.9   716.9   104.3  716.64   111.9  717.37   113.4  717.51
   122.5  719.88   131.6  722.98   140.7  725.96   149.8  728.61   159.5  731.38
   169.2  734.17   178.9  736.88   188.5  739.61   198.2  742.48
#Mann= 3 , 0 , 0
       0      .1       0    95.1    .045       0   113.4      .1       0
Bank Sta=95.1,113.4
XS Rating Curve= 0 ,0
Exp/Cntr=0.3,0.1