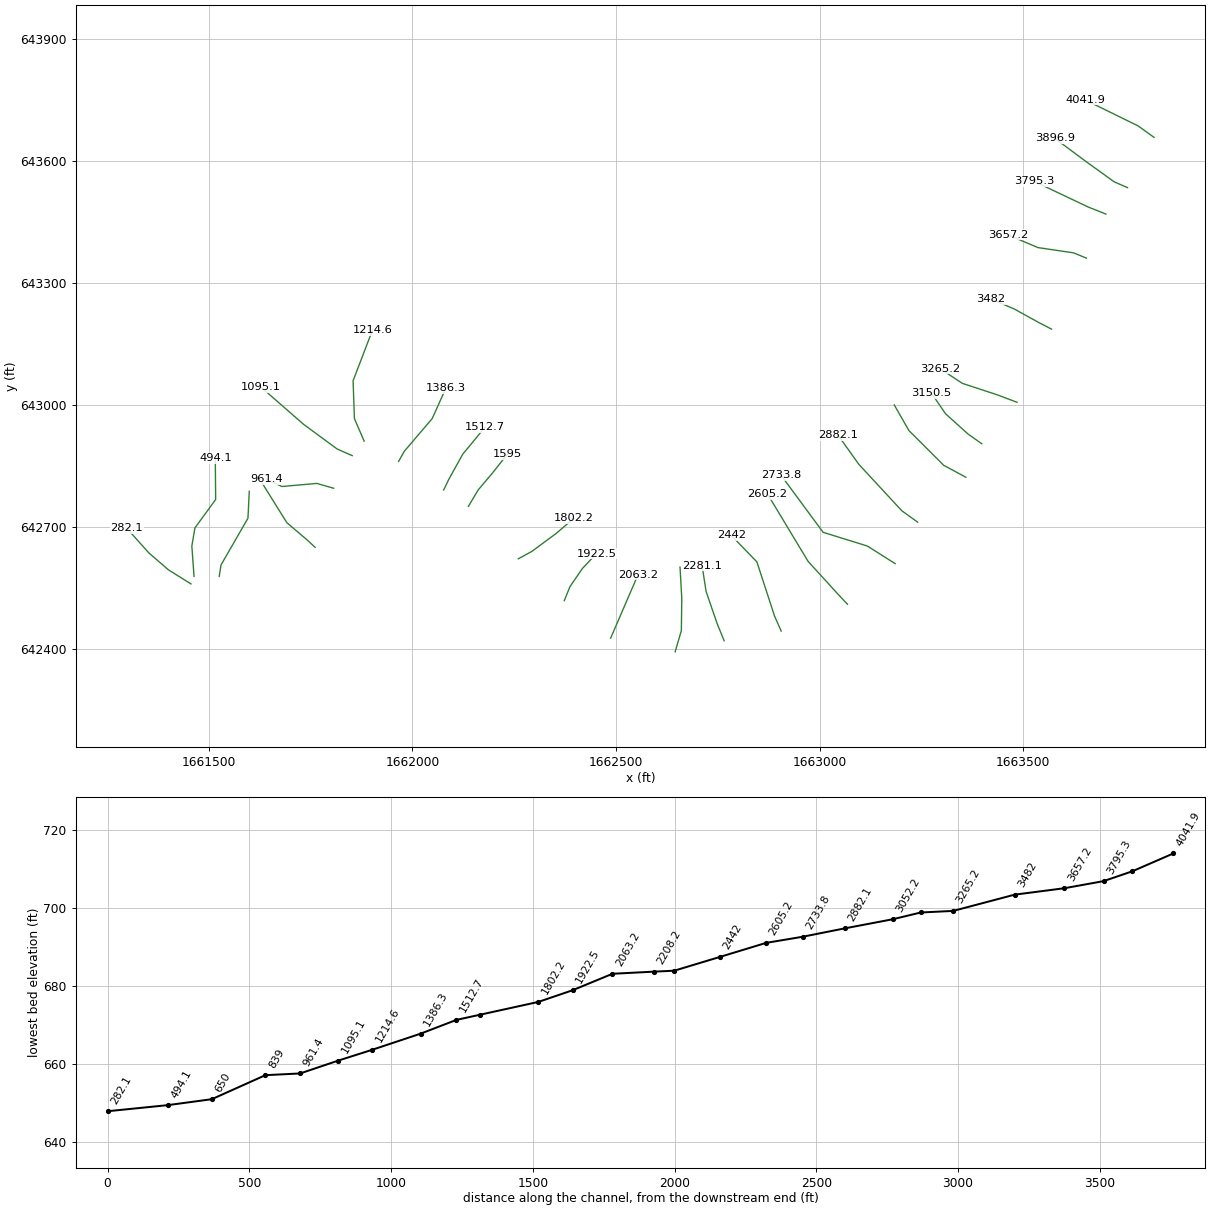
HEC-RAS study PNTRSRN.prj: PNTRSRN

--- PNTRSRN.g01 (geometry) --- (continued)

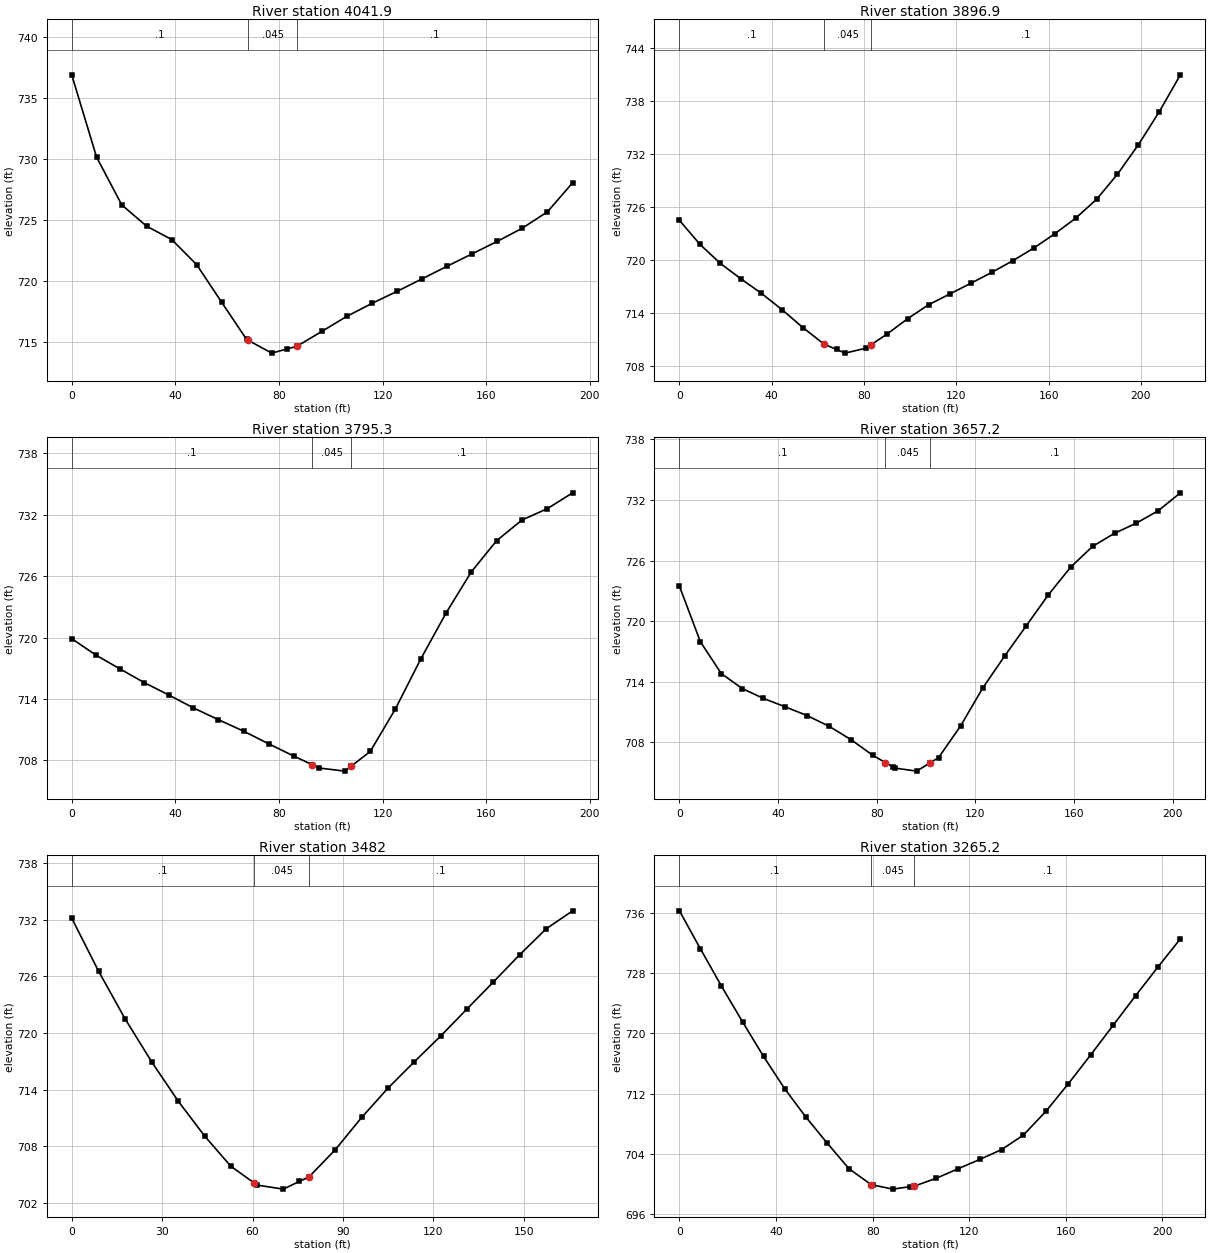
Type RM Length L Ch R = 1 ,4041.9  ,148.2,145,140.9
XS GIS Cut Line= 3
     1663821.346      643658.808     1663782.284       643687.02
     1663652.075      643751.039
#Sta/Elev= 23
       0  736.89     9.6  730.14    19.3  726.23    28.9  724.48    38.6  723.38
    48.2  721.33    57.9  718.23    67.5  715.19    68.2  715.11    77.2  714.07
    83.2  714.42    86.9  714.63    96.6  715.86   106.2  717.09   115.9  718.15
   125.6  719.14   135.2  720.16   144.9   721.2   154.6  722.22   164.3  723.24
   173.9  724.32   183.6  725.66   193.3  728.04
#Mann= 3 , 0 , 0
       0      .1       0    68.2    .045       0    86.9      .1       0
Bank Sta=68.2,86.9
XS Rating Curve= 0 ,0
Exp/Cntr=0.3,0.1

Type RM Length L Ch R = 1 ,3896.9  ,97.1,101.6,105.7
XS GIS Cut Line= 4
     1663756.242      643535.111      1663723.69      643549.216
     1663657.501       643596.96     1663577.205      643656.638
#Sta/Elev= 27
       0  724.48     8.9  721.76    17.7  719.62    26.6  717.88    35.5  716.24
    44.5  714.38    53.6  712.34    62.7  710.49    68.1  709.89    71.8  709.48
    80.8  710.04    83.1  710.44    89.9  711.62      99  713.39     108  714.95
   117.1  716.15   126.2  717.36   135.3  718.59   144.4  719.91   153.5  721.34
   162.6  722.95   171.7  724.72   180.8  726.86   189.8  729.68   198.9  733.02
     208  736.77   217.1  740.92
#Mann= 3 , 0 , 0
       0      .1       0    62.7    .045       0    83.1      .1       0
Bank Sta=62.7,83.1
XS Rating Curve= 0 ,0
Exp/Cntr=0.3,0.1

Type RM Length L Ch R = 1 ,3795.3  ,131.6,138.2,144.3
XS GIS Cut Line= 3
     1663703.073      643470.006     1663659.671      643487.368
     1663527.292      643550.302
#Sta/Elev= 23
       0   719.9     9.4  718.28    18.7  716.93      28   715.6    37.4   714.4
    46.8  713.15    56.5  711.99    66.3  710.86    76.1  709.61    85.8  708.41
    92.8  707.58    95.6  707.25   105.4  706.95   107.8  707.42   115.2  708.87
   124.9  713.02   134.7  717.91   144.5  722.42   154.2  726.42     164  729.48
   173.8   731.5   183.6  732.61   193.3  734.15
#Mann= 3 , 0 , 0
       0      .1       0    92.8    .045       0   107.8      .1       0
Bank Sta=92.8,107.8
XS Rating Curve= 0 ,0
Exp/Cntr=0.3,0.1

Type RM Length L Ch R = 1 ,3657.2  ,183.1,175.2,166.8
XS GIS Cut Line= 4
      1663655.33      643361.499     1663623.863       643374.52
     1663535.973      643387.541     1663462.188      643419.008
#Sta/Elev= 27
       0  723.45     8.5  717.94      17  714.79    25.5  713.31      34  712.34
    42.9   711.5    51.8  710.63    60.7  709.57    69.6  708.24    78.5  706.68
   83.48705.9803    86.4  705.57    87.4  705.43    96.2  705.13   101.4  705.92
   105.1  706.48     114  709.61   122.9  713.34   131.8  716.52   140.7  719.56
   149.6  722.61   158.6  725.34   167.5   727.4   176.4   728.7   185.3  729.71
   194.2  730.95   203.1  732.71
#Mann= 3 , 0 , 0
       0      .1       0   83.48    .045       0   101.4      .1       0
Bank Sta=83.48,101.4
XS Rating Curve= 0 ,0
Exp/Cntr=0.3,0.1

Type RM Length L Ch R = 1 ,3482    ,212.2,216.8,220.7
XS GIS Cut Line= 4
      1663569.61      643186.803     1663538.143      643203.079
     1663477.379      643236.716     1663420.955      643260.588
#Sta/Elev= 22
       0  732.15     8.9  726.54    17.7   721.5    26.6  716.91    35.4  712.76
    44.1   709.1    52.8   705.9    60.5  704.14    61.5  703.91    70.2  703.48
    75.5  704.29    78.8  704.79    87.5  707.67    96.2  711.06   104.9  714.15
   113.6  716.93   122.4  719.67   131.1  722.52   139.9  725.39   148.6  728.26
   157.4  731.01   166.2  732.92
#Mann= 3 , 0 , 0
       0      .1       0    60.5    .045       0    78.8      .1       0
Bank Sta=60.5,78.8
XS Rating Curve= 0 ,0
Exp/Cntr=0.3,0.1

Type RM Length L Ch R = 1 ,3265.2  ,123.5,114.6,105
XS GIS Cut Line= 4
     1663484.975      643006.682     1663436.146      643025.128
     1663350.426       643053.34     1663296.172      643089.147
#Sta/Elev= 26
       0  736.29     8.7  731.22    17.4  726.28    26.1  721.55    34.8  716.95
    43.5  712.68    52.2  708.94    61.2  705.41    70.2  702.02    79.3  699.92
    80.3  699.85    88.3  699.31    95.3  699.63    97.3  699.72   106.3  700.75
   115.4  702.02   124.4  703.26   133.4  704.57   142.4  706.49   151.7  709.64
     161  713.31   170.3  717.16   179.6  721.09   188.9  725.03   198.2  728.86
   207.4  732.57
#Mann= 3 , 0 , 0
       0      .1       0    79.3    .045       0    97.3      .1       0
Bank Sta=79.3,97.3
XS Rating Curve= 0 ,0
Exp/Cntr=0.3,0.1

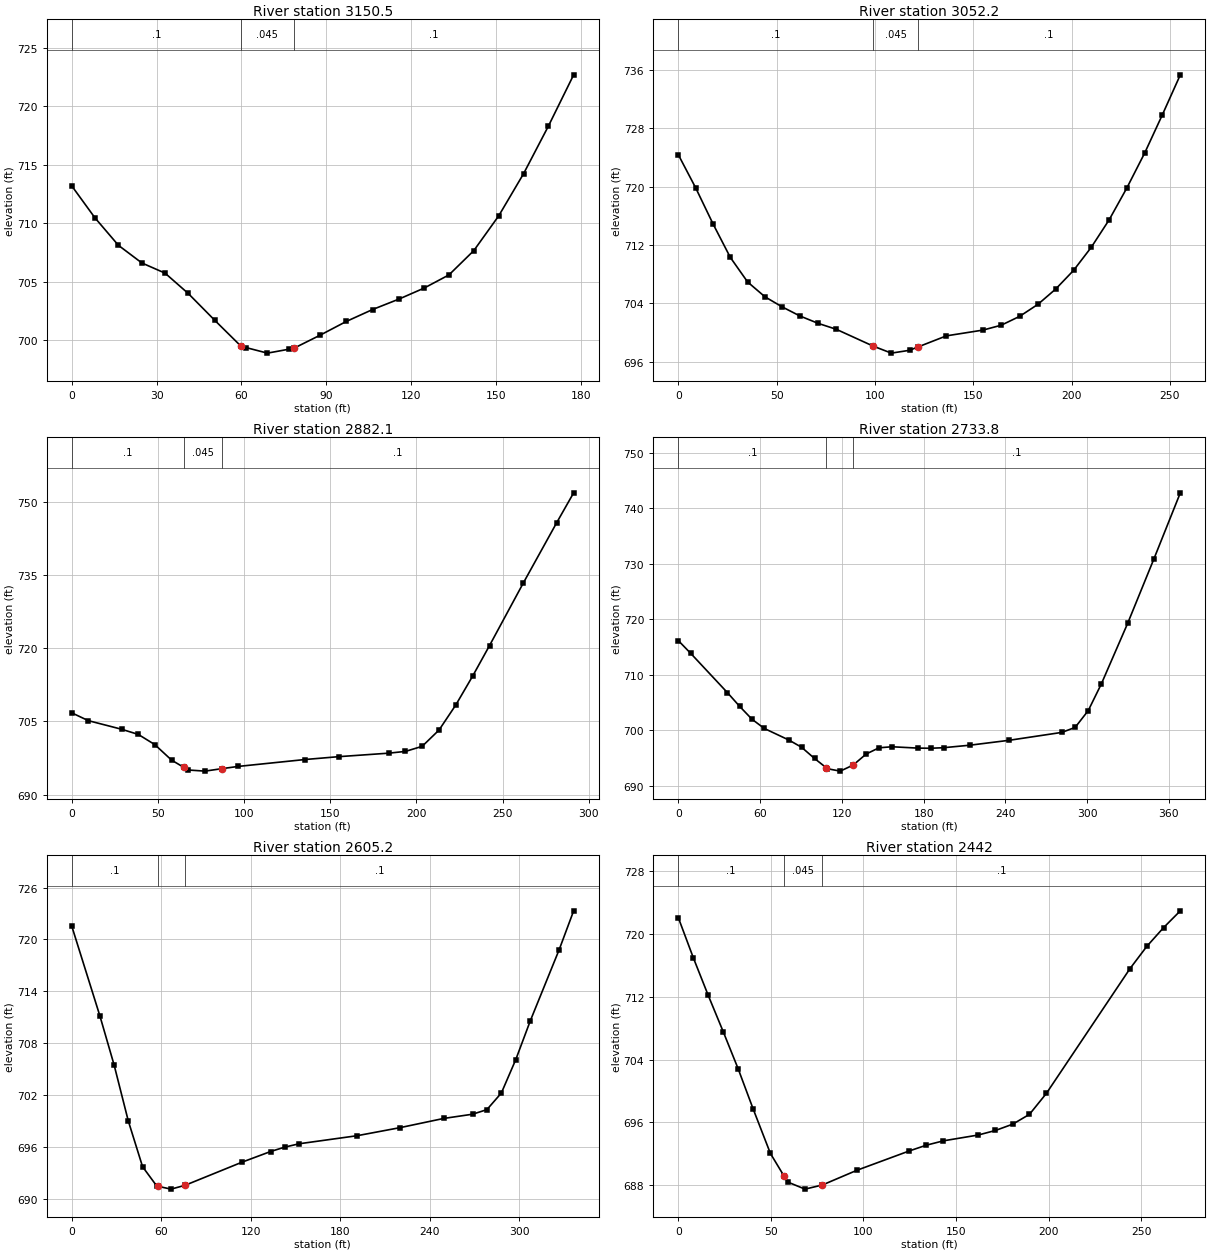
Type RM Length L Ch R = 1 ,3150.5  ,99.6,98.4,96.5
XS GIS Cut Line= 4
     1663398.169      642904.685     1663364.532      642928.557
     1663309.193       642978.47     1663274.471      643029.468
#Sta/Elev= 23
       0   713.2     8.2  710.47    16.5  708.12    24.8  706.61      33  705.74
    41.2     704    50.6   701.7    59.9  699.48    61.7  699.37    69.2   698.9
    76.7  699.23    78.5  699.31    87.8  700.43    97.1  701.61   106.4  702.63
   115.8  703.53   124.6  704.46   133.4  705.59   142.2  707.67     151  710.64
   159.8  714.25   168.6  718.33   177.5   722.7
#Mann= 3 , 0 , 0
       0      .1       0    59.9    .045       0    78.5      .1       0
Bank Sta=59.9,78.5
XS Rating Curve= 0 ,0
Exp/Cntr=0.3,0.1

Type RM Length L Ch R = 1 ,3052.2  ,168.8,170,169.2
XS GIS Cut Line= 4
     1663359.106       642822.22     1663304.853      642851.517
     1663219.132      642937.237     1663183.325      643000.171
#Sta/Elev= 27
       0  724.36     8.8  719.83    17.6   714.9    26.4   710.3    35.2  706.93
      44   704.9    52.8  703.51    61.7  702.28      71  701.26    80.3  700.44
      99  698.14   108.3  697.17   117.6  697.56   121.8  698.01   136.3  699.54
   154.9  700.33   164.2     701   173.6  702.22   182.9  703.87   191.9  705.96
     201  708.52     210  711.69   219.1  715.46   228.1  719.83   237.2  724.64
   246.2  729.89   255.3  735.35
#Mann= 3 , 0 , 0
       0      .1       0      99    .045       0   121.8      .1       0
Bank Sta=99,121.8
XS Rating Curve= 0 ,0
Exp/Cntr=0.3,0.1

Type RM Length L Ch R = 1 ,2882.1  ,135.1,148.3,160
XS GIS Cut Line= 4
     1663240.834      642711.543     1663201.771      642739.755
      1663096.52      642853.687     1663045.521      642925.302
#Sta/Elev= 23
       0  706.76     9.6  705.16    28.9   703.4    38.6  702.34    48.2  700.25
    57.9  697.08      65  695.59    67.6  695.05    77.3  694.82      87  695.32
    96.7  695.79   135.4   697.2   154.8  697.78   183.9   698.5   193.6  698.86
   203.3   699.9   213.1  703.24   222.8  708.36   232.6  714.29   242.4  720.55
   261.9   733.3   281.4  745.74   291.2  751.83
#Mann= 3 , 0 , 0
       0      .1       0      65    .045       0      87      .1       0
Bank Sta=65,87
XS Rating Curve= 0 ,0
Exp/Cntr=0.3,0.1

Type RM Length L Ch R = 1 ,2733.8  ,140.3,128.6,116.2
XS GIS Cut Line= 4
     1663185.495      642609.546     1663117.136      642652.949
     1663008.629      642686.586     1662905.547       642826.56
#Sta/Elev= 28
       0  716.17       9  713.89      36   706.8      45  704.32      54  702.02
      63  700.36      81  698.28    90.4  696.97    99.9  694.95   108.5  693.28
   109.4   693.1   118.8  692.67   128.3  693.77   137.8  695.75   147.2  696.87
   156.7  697.06   175.6  696.82   185.1  696.79   194.6  696.89   213.9  697.34
   242.9  698.23   281.5  699.65   291.2  700.55   300.8  703.57   310.5  708.42
   329.8  719.33   349.1  730.96   368.4  742.81
#Mann= 3 , 0 , 0
       0      .1       0   108.5    .045       0   128.3      .1       0
Bank Sta=108.5,128.3
XS Rating Curve= 0 ,0
Exp/Cntr=0.3,0.1

Type RM Length L Ch R = 1 ,2605.2  ,173.4,163.2,150.4
XS GIS Cut Line= 4
     1663068.308       642509.72     1663048.777      642530.336
     1662971.737      642614.972      1662871.91      642780.987
#Sta/Elev= 23
       0  721.54    18.9  711.13    28.4  705.47    37.9     699    47.5  693.69
      57  691.46    57.7  691.43    66.6   691.1    76.1  691.55   114.2  694.22
   133.3  695.45   142.8  695.96   152.5  696.35   191.3  697.28   220.3  698.22
   249.4  699.28   268.8  699.77   278.4   700.3   288.1  702.22   297.8   706.1
   307.5  710.57   326.9  718.82   336.6  723.31
#Mann= 3 , 0 , 0
       0      .1       0    57.7    .045       0    76.1      .1       0
Bank Sta=57.7,76.1
XS Rating Curve= 0 ,0
Exp/Cntr=0.3,0.1

Type RM Length L Ch R = 1 ,2442    ,159.2,160.8,161.2
XS GIS Cut Line= 4
     1662905.547      642443.531     1662889.271      642480.423
     1662845.869      642613.887     1662782.935      642678.991
#Sta/Elev= 24
       0  722.07     8.1  716.96    16.1   712.2    24.2  707.57    32.3  702.82
    40.3  697.76    49.7  692.04    56.9  689.22      59   688.4    68.4  687.49
    77.8  688.02    96.5   689.9   124.5  692.34   133.9  693.09   143.2  693.65
     162  694.39   171.3  694.97   180.7  695.78   189.7  697.03   198.8  699.69
     244  715.61   253.1  718.45   262.2  720.85   271.2  722.98
#Mann= 3 , 0 , 0
       0      .1       0    56.9    .045       0    77.8      .1       0
Bank Sta=56.9,77.8
XS Rating Curve= 0 ,0
Exp/Cntr=0.3,0.1

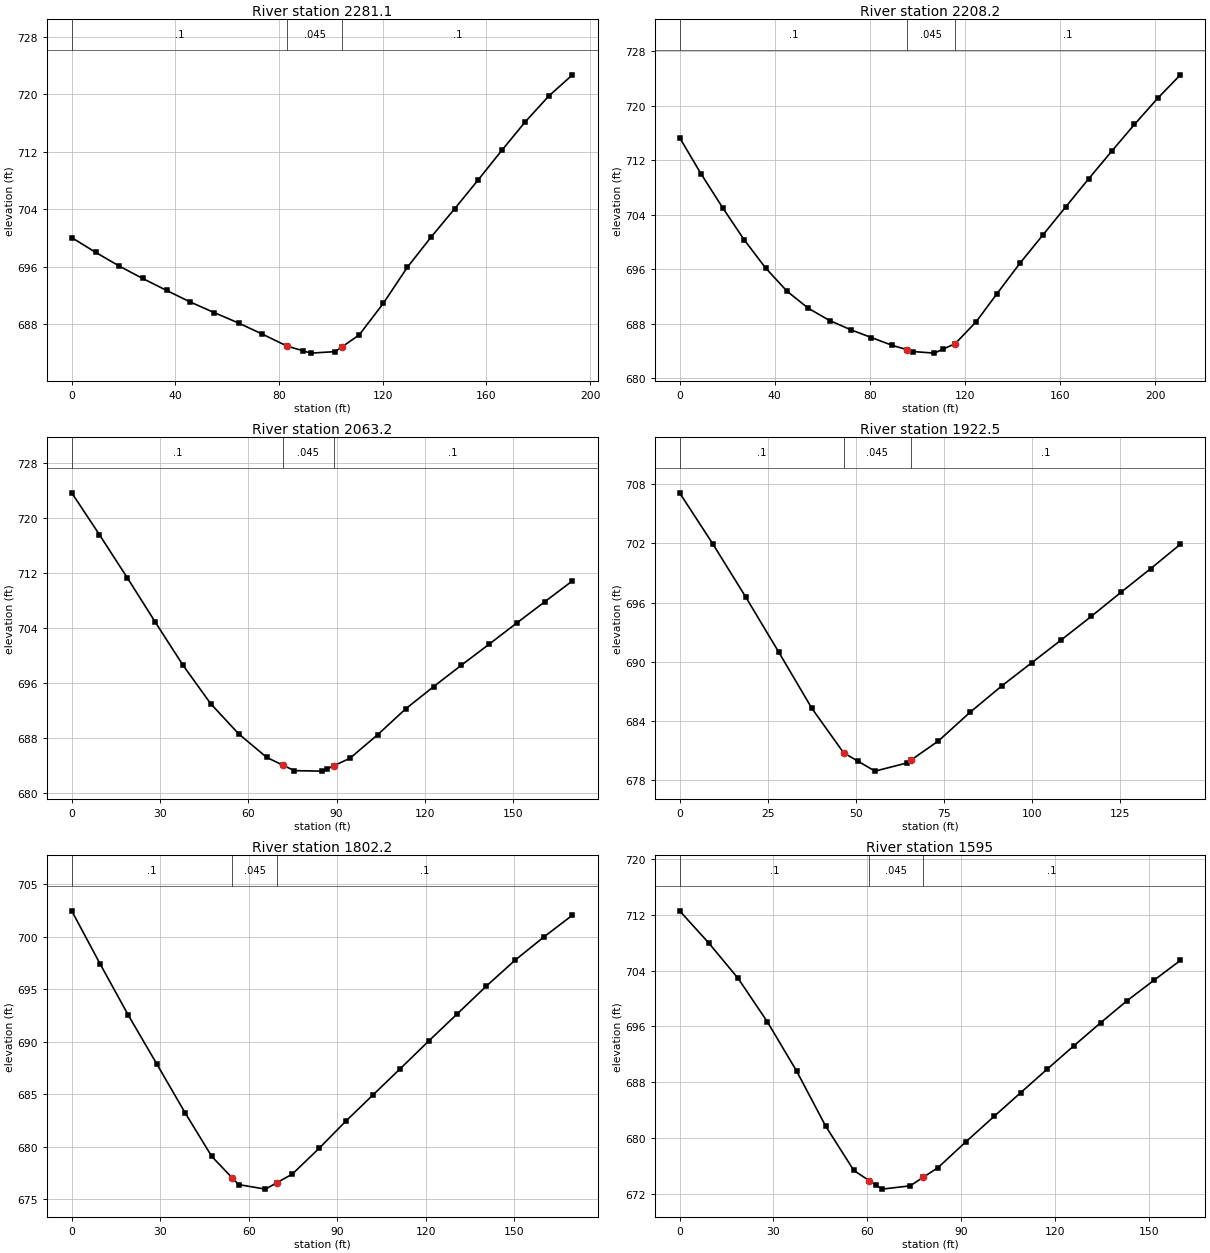
Type RM Length L Ch R = 1 ,2281.1  ,80.6,72.9,65
XS GIS Cut Line= 4
     1662765.573      642419.659     1662748.212      642461.977
     1662721.086      642541.187      1662711.32      642604.121
#Sta/Elev= 24
       0  700.06     9.2  698.01    18.3   696.1    27.4  694.36    36.6   692.7
    45.7  691.09      55   689.6    64.4  688.15    73.6   686.6      83  684.95
    89.3  684.28    92.3  683.96   101.6  684.17   104.3  684.84   110.9  686.49
   120.2  690.89   129.5  695.93   138.6  700.11   147.7  704.06   156.8  708.09
   165.9   712.2     175   716.2   184.1   719.8   193.2  722.74
#Mann= 3 , 0 , 0
       0      .1       0      83    .045       0   104.3      .1       0
Bank Sta=83,104.3
XS Rating Curve= 0 ,0
Exp/Cntr=0.3,0.1

Type RM Length L Ch R = 1 ,2208.2  ,153.8,145,135.9
XS GIS Cut Line= 4
     1662645.131      642392.532     1662660.322      642444.616
     1662661.407      642523.826     1662657.067      642600.866
#Sta/Elev= 26
       0  715.32       9  710.01    18.1  705.04    27.1  700.36    36.2  696.18
    45.2  692.78    54.2  690.27    63.1  688.49    71.9  687.15    80.7  685.99
    89.5  684.84    95.8   684.2    98.3  683.94   107.1  683.71   110.8  684.29
   115.9   685.1   124.7   688.3   133.5  692.44   143.1  696.88   152.8  701.04
   162.4  705.16     172  709.26   181.7  713.31   191.3  717.25     201  721.06
   210.6  724.52
#Mann= 3 , 0 , 0
       0      .1       0    95.8    .045       0   115.9      .1       0
Bank Sta=95.8,115.9
XS Rating Curve= 0 ,0
Exp/Cntr=0.3,0.1

Type RM Length L Ch R = 1 ,2063.2  ,144.4,140.8,136
XS GIS Cut Line= 2
     1662486.711       642426.17     1662553.985       642582.42
#Sta/Elev= 22
       0  723.68     9.4   717.6    18.9   711.3    28.4  704.85    37.8  698.59
    47.2  692.99    56.7   688.6    66.2  685.18    71.8  684.02    75.6  683.24
    85.1  683.17    86.8  683.51   88.96683.9392    94.5  685.04     104   688.5
   113.4  692.22   122.9  695.46   132.3  698.57   141.8  701.65   151.2  704.74
   160.7  707.83   170.1  710.87
#Mann= 3 , 0 , 0
       0      .1       0    71.8    .045       0   88.96      .1       0
Bank Sta=71.8,88.96
XS Rating Curve= 0 ,0
Exp/Cntr=0.3,0.1

Type RM Length L Ch R = 1 ,1922.5  ,127.9,120.3,112.5
XS GIS Cut Line= 4
     1662372.778      642518.401     1662386.884      642553.123
     1662417.266      642597.611     1662451.988      642634.503
#Sta/Elev= 19
       0  707.12     9.4  701.96    18.7   696.6    28.1     691    37.5   685.3
    46.5   680.8    50.5  679.96    55.4  678.94    64.4  679.76    65.5  680.03
    73.4     682    82.4  684.91    91.4  687.58    99.8   689.9   108.2  692.22
   116.7   694.6   125.1  697.03   133.6  699.45     142  701.91
#Mann= 3 , 0 , 0
       0      .1       0    46.5    .045       0    65.5      .1       0
Bank Sta=46.5,65.5
XS Rating Curve= 0 ,0
Exp/Cntr=0.3,0.1

Type RM Length L Ch R = 1 ,1802.2  ,201.8,207.2,212.4
XS GIS Cut Line= 4
     1662259.931      642621.482     1662293.568      642639.928
     1662352.162      642683.331      1662396.65      642721.308
#Sta/Elev= 21
       0  702.45     9.6  697.41    19.2  692.51    28.8  687.89    38.4  683.24
    47.5  679.06    54.5     677    56.6  676.38    65.7  675.95    69.5  676.55
    74.8  677.38    83.9  679.84      93  682.44   102.2  684.93   111.3  687.39
     121  690.04   130.8  692.66   140.5  695.26   150.3  697.74     160  699.94
   169.8  702.04
#Mann= 3 , 0 , 0
       0      .1       0    54.5    .045       0    69.5      .1       0
Bank Sta=54.5,69.5
XS Rating Curve= 0 ,0
Exp/Cntr=0.3,0.1

Type RM Length L Ch R = 1 ,1595    ,77.3,82.2,86.1
XS GIS Cut Line= 4
     1662137.318      642750.605      1662161.19      642790.753
     1662195.912      642831.986     1662232.804      642878.644
#Sta/Elev= 22
       0  712.57     9.3  707.97    18.7  702.88      28  696.69    37.4  689.59
    46.7  681.68    55.7  675.32   60.58673.8698    62.8  673.21    64.7  672.64
    73.7  673.11    77.8  674.31    82.6  675.72    91.6  679.46   100.6   683.1
   109.1   686.5   117.6  689.89   126.1  693.22   134.6  696.51   143.1  699.69
   151.6  702.59   160.1  705.45
#Mann= 3 , 0 , 0
       0      .1       0   60.58    .045       0    77.8      .1       0
Bank Sta=60.58,77.8
XS Rating Curve= 0 ,0
Exp/Cntr=0.3,0.1

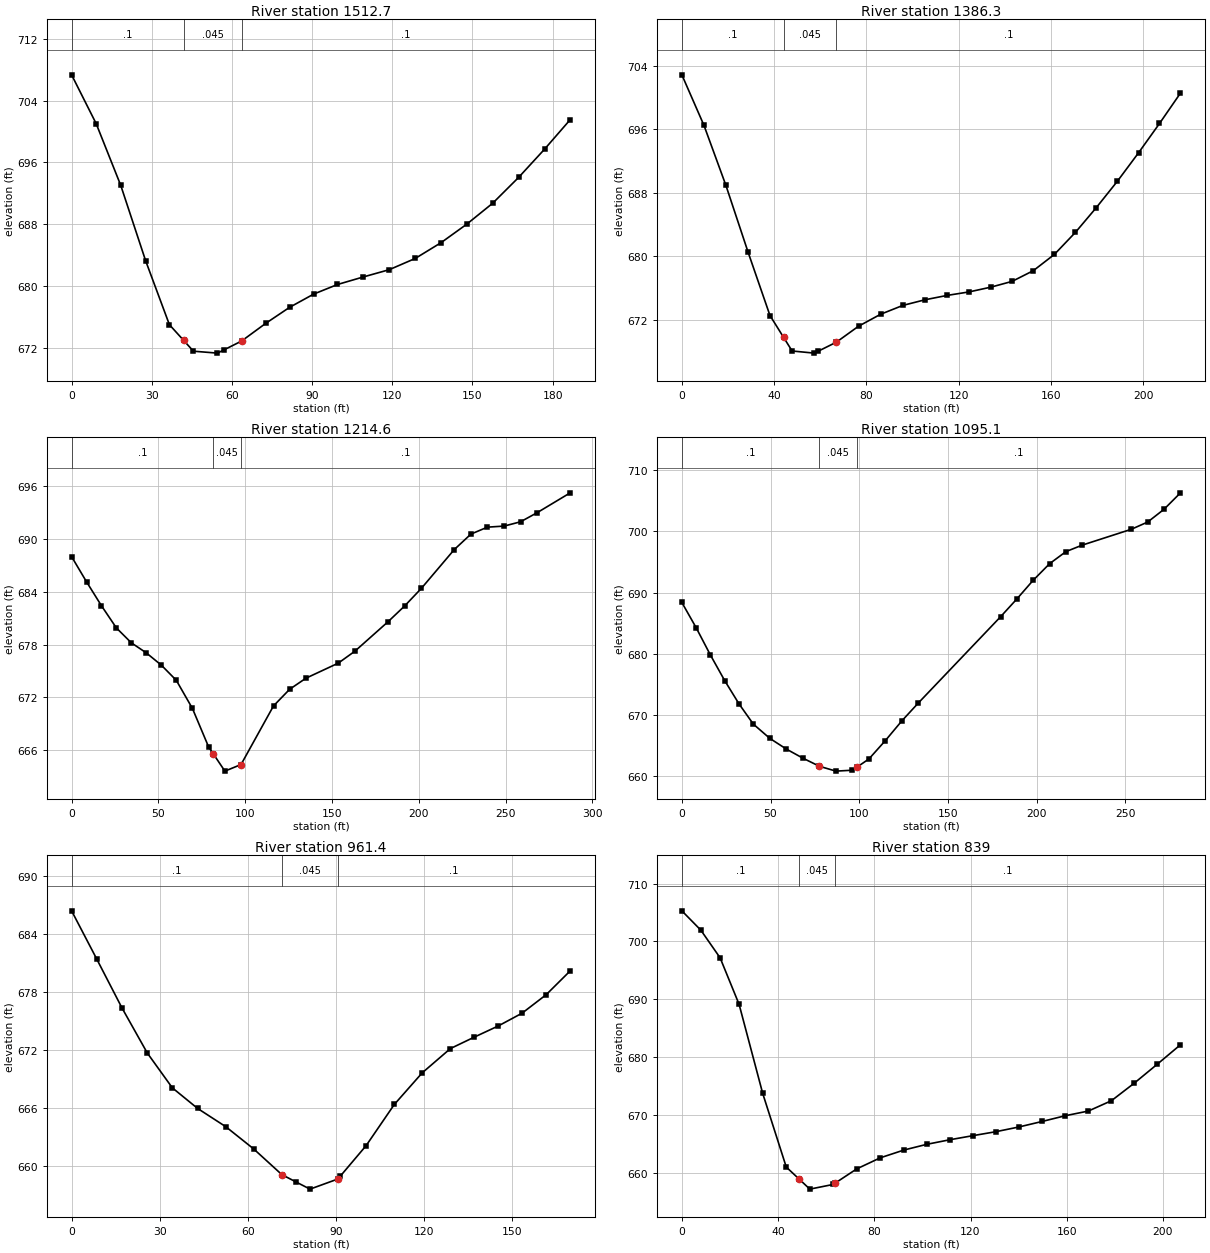
Type RM Length L Ch R = 1 ,1512.7  ,130.7,126.4,121.6
XS GIS Cut Line= 4
     1662076.554      642790.753      1662088.49       642815.71
     1662123.212      642878.644     1662178.551      642945.918
#Sta/Elev= 23
       0  707.34     9.2  701.02    18.4  693.03    27.7  683.29    36.6  675.01
    41.9  672.99    45.6  671.58    54.6  671.33    56.9  671.73    63.6  672.89
    72.6  675.17    81.6  677.26    90.6  678.97    99.5  680.21   109.2  681.19
   118.9  682.13   128.6  683.58   138.3  685.63   147.9  688.02   157.6  690.73
   167.3  694.07     177  697.72   186.6  701.54
#Mann= 3 , 0 , 0
       0      .1       0    41.9    .045       0    63.6      .1       0
Bank Sta=41.9,63.6
XS Rating Curve= 0 ,0
Exp/Cntr=0.3,0.1

Type RM Length L Ch R = 1 ,1386.3  ,154.5,171.7,188
XS GIS Cut Line= 4
     1661965.877      642861.282     1661979.983      642886.239
     1662048.343      642966.534      1662081.98      643041.404
#Sta/Elev= 26
       0  702.85     9.6  696.47    19.1  688.92    28.7  680.52    38.2  672.53
    44.1  669.78    47.8  668.06    57.4  667.79    59.1  668.03      67  669.17
    76.6  671.18    86.2  672.69    95.8   673.8   105.4  674.51     115  675.06
   124.5   675.5   134.1  676.11   143.2  676.83   152.4  678.18   161.5  680.22
   170.6  682.99   179.7  686.12   188.8  689.43     198  693.02   207.1  696.72
   216.2  700.55
#Mann= 3 , 0 , 0
       0      .1       0    44.1    .045       0      67      .1       0
Bank Sta=44.1,67
XS Rating Curve= 0 ,0
Exp/Cntr=0.3,0.1

Type RM Length L Ch R = 1 ,1214.6  ,98.5,119.5,139.5
XS GIS Cut Line= 4
     1661881.242      642911.196      1661857.37      642966.534
     1661854.115       643059.85     1661901.858      643184.633
#Sta/Elev= 28
       0     688     8.6  685.14    17.2  682.42    25.8   679.9    34.4  678.21
      43  677.07    51.7  675.67    60.3  673.95    69.6  670.75    78.9  666.39
    81.7  665.57    88.3  663.63    97.6  664.38   116.3  671.04   125.6  672.93
     135  674.19   153.6   675.9   163.2  677.26   182.3  680.61   191.8  682.39
   201.4  684.38   220.4   688.8     230  690.56   239.5  691.35   249.1  691.47
   258.6  691.96   268.2     693   287.2  695.25
#Mann= 3 , 0 , 0
       0      .1       0    81.7    .045       0    97.6      .1       0
Bank Sta=81.7,97.6
XS Rating Curve= 0 ,0
Exp/Cntr=0.3,0.1

Type RM Length L Ch R = 1 ,1095.1  ,116.8,133.7,149.6
XS GIS Cut Line= 4
     1661851.945      642875.388     1661815.053      642891.664
     1661732.587      642952.428     1661628.421      643043.574
#Sta/Elev= 27
       0   688.4     8.1  684.26    16.1  679.82    24.2  675.62    32.3  671.81
    40.3  668.54    49.6  666.21      59  664.45    68.3  662.97    77.6  661.65
    86.9  660.86    96.2  661.01    98.6  661.48   105.5  662.85   114.8  665.86
   124.1  669.08   133.4     672   179.7  686.06   188.9  688.97   198.1  692.02
   207.4  694.74   216.6  696.71   225.8  697.77   253.5  700.36   262.7  701.54
   271.9  703.62   281.2  706.31
#Mann= 3 , 0 , 0
       0      .1       0    77.6    .045       0    98.6      .1       0
Bank Sta=77.6,98.6
XS Rating Curve= 0 ,0
Exp/Cntr=0.3,0.1

Type RM Length L Ch R = 1 ,961.4   ,140.6,122.4,104.1
XS GIS Cut Line= 4
     1661806.372      642795.093     1661765.139      642807.029
     1661679.419      642799.433     1661642.527      642816.795
#Sta/Elev= 22
       0  686.37     8.6  681.36    17.2   676.3    25.8  671.65    34.3  668.06
    42.9  665.93    52.5  664.04      62  661.74    71.6  659.08    76.5  658.31
    81.2  657.58    90.7  658.63    91.5  658.92   100.3  662.08   109.9  666.34
   119.4  669.61     129  672.12   137.1   673.3   145.3  674.46   153.4  675.78
   161.6  677.69   169.8  680.16
#Mann= 3 , 0 , 0
       0      .1       0    71.6    .045       0    90.7      .1       0
Bank Sta=71.6,90.7
XS Rating Curve= 0 ,0
Exp/Cntr=0.3,0.1

Type RM Length L Ch R = 1 ,839     ,220.6,189,156.4
XS GIS Cut Line= 4
     1661760.799      642649.694     1661743.438       642665.97
     1661691.355      642710.458     1661630.591      642808.114
#Sta/Elev= 25
       0  705.29     7.9  701.94    15.9  697.16    23.8   689.1    33.6  673.71
    43.4  660.96    48.8  658.86    53.2  657.14    62.9  657.95    63.8   658.2
    72.7  660.64    82.5  662.56    92.3   663.9   101.9   664.9   111.5  665.69
     121  666.39   130.6  667.08   140.2   667.9   149.8  668.85   159.4  669.84
     169  670.65   178.6  672.44   188.1  675.48   197.7  678.77   207.3  682.12
#Mann= 3 , 0 , 0
       0      .1       0    48.8    .045       0    63.8      .1       0
Bank Sta=48.8,63.8
XS Rating Curve= 0 ,0
Exp/Cntr=0.3,0.1

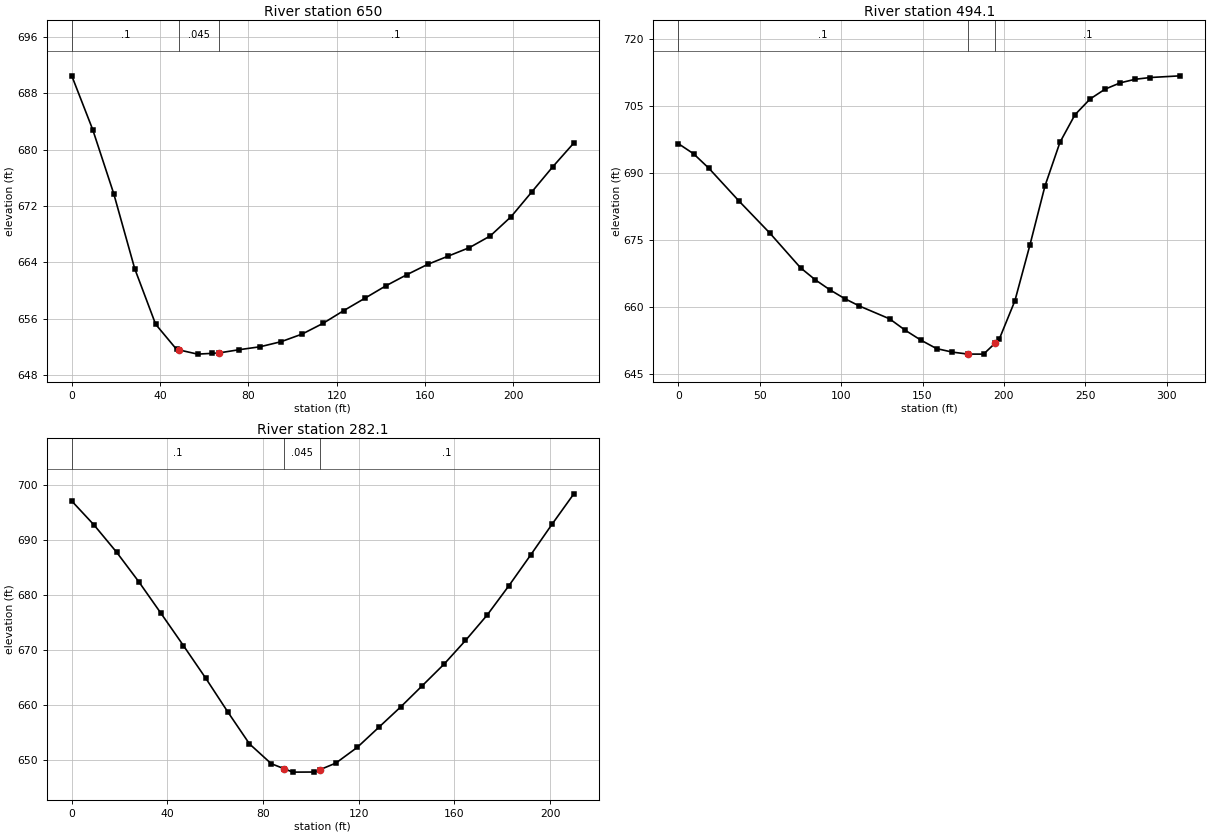
Type RM Length L Ch R = 1 ,650     ,146.4,155.9,156.3
XS GIS Cut Line= 4
     1661525.339      642578.079     1661529.679      642606.291
     1661595.869      642721.308     1661599.124      642787.498
#Sta/Elev= 27
       0  690.47     9.5  682.83      19  673.76    28.5  663.12      38  655.21
    47.5  651.64    48.7  651.56      57  650.97    63.7  651.08    66.5  651.13
    75.9   651.6    85.4  652.02    94.9  652.74   104.4  653.82   113.8  655.33
   123.3  657.16   132.8   658.9   142.3  660.66   151.8  662.24   161.2   663.7
   170.7   664.9   180.2  666.09   189.6  667.74   199.1  670.49   208.6  674.05
     218  677.58   227.5  680.94
#Mann= 3 , 0 , 0
       0      .1       0    48.7    .045       0    66.5      .1       0
Bank Sta=48.7,66.5
XS Rating Curve= 0 ,0
Exp/Cntr=0.3,0.1

Type RM Length L Ch R = 1 ,494.1   ,181.3,212,243.4
XS GIS Cut Line= 5
      1661463.49      642578.079     1661458.065      642652.949
      1661465.66      642697.437     1661516.543      642767.409
     1661515.675      642868.972
#Sta/Elev= 30
       0  696.54     9.4  694.26    18.8  691.02    37.5  683.61    56.3  676.49
    75.1  668.75    84.1  666.08    93.1  663.83   102.2  661.86   111.2  660.21
   129.8  657.33   139.4  654.78     149  652.57   158.6  650.68   168.3  649.89
   177.9  649.45   187.5  649.44   194.6   651.9   197.1  652.77   206.7  661.34
     216  673.91   225.2  687.06   234.4  696.82   243.6  702.98   252.9  706.51
   262.1  708.71   271.4  710.12   280.6  710.92   289.8  711.31   308.3  711.69
#Mann= 3 , 0 , 0
       0      .1       0   177.9    .045       0   194.6      .1       0
Bank Sta=177.9,194.6
XS Rating Curve= 0 ,0
Exp/Cntr=0.3,0.1

Type RM Length L Ch R = 1 ,282.1   ,192.1,182.4,173
XS GIS Cut Line= 4
     1661455.895      642559.633     1661400.556      642594.355
     1661352.813      642635.588      1661298.56      642696.352
#Sta/Elev= 26
       0  697.08     9.3  692.74    18.7  687.82      28  682.45    37.3   676.7
    46.7  670.83      56  664.93    65.3  658.76    74.3     653    83.4  649.41
    88.9  648.48    92.4  647.88   101.4   647.9   103.9  648.35   110.4  649.52
   119.4  652.39   128.4  656.03   137.5  659.71   146.5  663.55   155.6  667.46
   164.6  671.77   173.7  676.41   182.7  681.68   191.8  687.26   200.8  692.88
   209.9  698.39
#Mann= 3 , 0 , 0
       0      .1       0    88.9    .045       0   103.9      .1       0
Bank Sta=88.9,103.9
XS Rating Curve= 0 ,0
Exp/Cntr=0.3,0.1