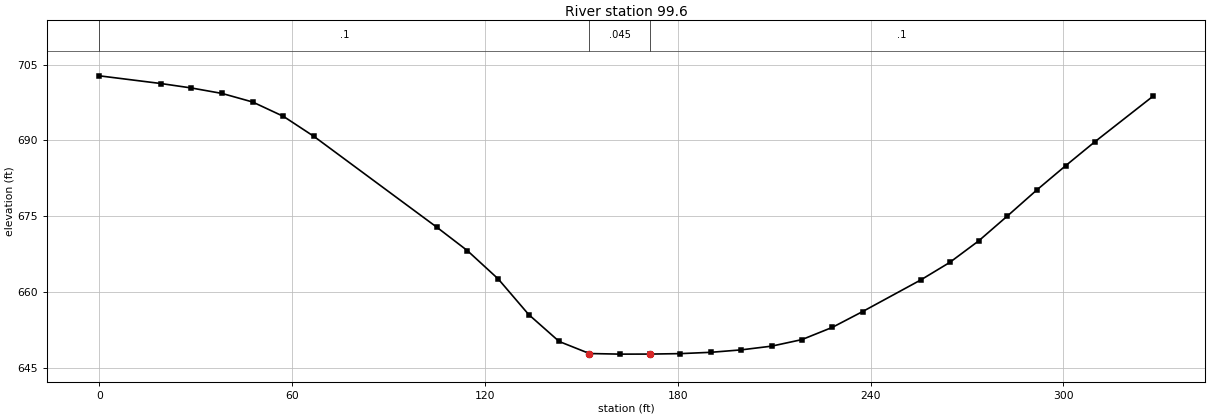
HEC-RAS study PNTRSRN.prj: PNTRSRN

--- PNTRSRN.g01 (geometry) --- (continued)

Type RM Length L Ch R = 1 ,99.6    ,106.8,99.6,92.2
XS GIS Cut Line= 4
     1661404.896      642458.722     1661271.433      642452.211
      1661228.03      642546.612     1661212.839      642635.588
#Sta/Elev= 30
       0  702.79    19.1  701.27    28.6  700.39    38.2   699.3    47.7  697.61
    57.3  694.76    66.8  690.79     105  672.83   114.5   668.2   124.1   662.6
   133.6  655.54   143.1   650.2   152.5  647.82     162   647.7   171.4  647.71
   180.8   647.8   190.3  648.06   199.7  648.54   209.2  649.28   218.6  650.57
   228.1     653   237.5  656.12   255.6  662.38   264.6  665.84   273.6   670.1
   282.6  675.06   291.7  680.18   300.7     685   309.7  689.69   327.8  698.71
#Mann= 3 , 0 , 0
       0      .1       0   152.5    .045       0   171.4      .1       0
Bank Sta=152.5,171.4
XS Rating Curve= 0 ,0
Exp/Cntr=0.3,0.1

Chan Stop Cuts=-1
Use User Specified Reach Order=0
Composite Channel Slope=5